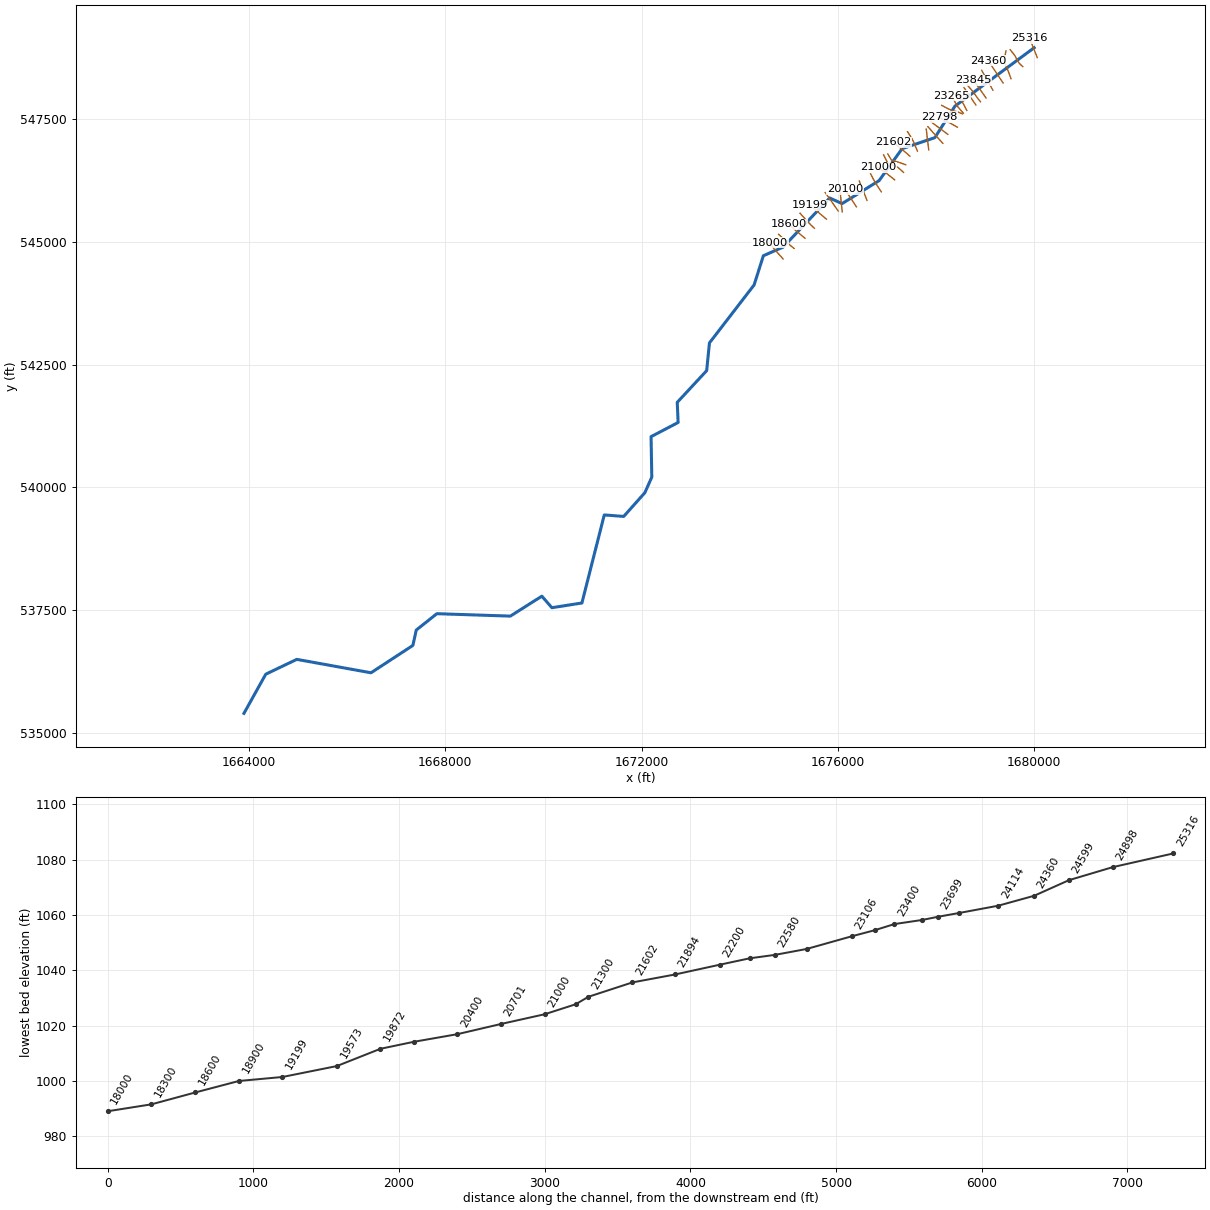
--- TurkeyRn.prj (project) ---

Proj Title=TurkeyRn
Current Plan=p01
Default Exp/Contr=0,0
English Units
Geom File=g01
Flow File=f01
Plan File=p01
BEGIN DESCRIPTION:
---------- MODELED AS PART OF WVEM CTP PROGRAM, 2025----------
Stream Name: Turkey Run
Flood Zone: AFH
Marshall County, WV
HEC-RAS Version: RAS 6.6
Vertical Datum: NAVD88
Projection: NAD 1983 StatePlane West Virginia N FIPS 4701 (US Feet)
Terrain: 1-meter West Virginia FEMA R3 South Central (collected 2018-2019)
Land Use: 2024 NLCD
Hydrologic Method:
Duda et al., "Estimation of magnitude and frequency of floods for rural, unregulated streams in and near Virginia and West Virginia." September 8, 2025.
Additional Model Notes:
Large dam near RS 1350
END DESCRIPTION:
DSS Export Rating Curves= 0
DSS Export Rating Curve Sorted= 0
DSS Export Volume Flow Curves= 0
DXF OffsetX= 0
DXF OffsetY= 0
DXF ScaleX= 0
DXF ScaleY= 0

--- TurkeyRn.p01 (plan) ---

Plan Title=Floodplain
Program Version=6.60
Short Identifier=Floodplain
Geom File=g01
Flow File=f01
Subcritical Flow
K Sum by GR= 0
Std Step Tol= 0.01
Critical Tol= 0.01
Num of Std Step Trials= 20
Max Error Tol= 0.3
Flow Tol Ratio= 0.001
Split Flow NTrial= 30
Split Flow Tol= 0.02
Split Flow Ratio= 0.02
Log Output Level= 0
Friction Slope Method= 1
Unsteady Friction Slope Method= 2
Unsteady Bridges Friction Slope Method= 1
Parabolic Critical Depth
Global Vel Dist= 0 , 0 , 0
Global Log Level= 0
CheckData=False
Encroach Param=-1 ,0,0, 0
Flow Ratio Tolerance=0.1
Flow Ratio Min Ratio=0.5
Flow Ratio Max Ratio=4
Flow Ratio Max Iterations= 10
Mapping Interval=1HOUR
Computation Time Step Use Courant=        0
Computation Time Step Use Time Series=    0
Computation Time Step Count To Double=0
Computation Time Step Max Doubling=0
Computation Time Step Max Halving=0
Computation Time Step Residence Courant=0
Run HTab= 0
Run UNet= 0
Run Sediment= 0
Run PostProcess= 0
Run WQNet= 0
Run RASMapper=-1
UNET Theta= 0
UNET Theta Warmup= 0
UNET ZTol= 0
UNET ZSATol= 0
UNET MxIter= 0
UNET Max Iter WO Improvement= 0
UNET MaxInSteps= 0
UNET DtIC= 0
UNET DtMin= 0
UNET MaxCRTS= 0
UNET WFStab= 0
UNET SFStab= 0
UNET WFX= 1
UNET SFX= 1
UNET Gravity=32.17405
UNET 1D Methodology=Finite Difference
UNET DSS MLevel= 1
UNET Pardiso=0
UNET DZMax Abort= 0
UNET Use Existing IB Tables= 0
UNET Froude Reduction=False
UNET Froude Limit= 0
UNET Froude Power= 0
UNET D1 Cores= 0
UNET WindReference=Eulerian
UNET WindDragFormulation=Hsu (1988)
UNET D2 Coriolis=0
UNET D2 Cores= 0
UNET D2 Theta= 1
UNET D2 Theta Warmup= 1
UNET D2 Z Tol= 0.01
UNET D2 Volume Tol= 0.01
UNET D2 Max Iterations= 20
UNET D2 Advanced Convergence=0
UNET D2 WS Max Tol=0.15
UNET D2 WS RMS Tol=0.002
UNET D2 WS Stall Tol=1
UNET D2 Equation= 0
UNET D2 RampUpFraction=0.1
UNET D2 TimeSlices= 1
UNET D2 Turbulence Formulation=Non-Conservative (original)
UNET D2 Eddy Viscosity=0.3
UNET D2 Transverse Eddy Viscosity=0.1
UNET D2 Smagorinsky Mixing=0
UNET D2 BCVolumeCheck=0
UNET D2 Cores=0
UNET D2 SolverType=PARDISO (Direct)
UNET D2 Minimum Iterations= 3
UNET D2 Maximum Iterations= 30
UNET D2 Restart Number= 10
UNET D2 Relaxation Coeff=1.3
UNET D2 SOR Precondition Iterations= 10
UNET D2 ILUT Maximum Fill= 8
UNET D2 ILUT Tolerance=1E-08
UNET D2 Convergence Tolerance=0.00001
PS Theta= 1
PS WS Tol= 0.01
PS Volume Tol= 0.01
PS Max Iterations= 20
PS Equation= 0
PS Advance Time Step=-1
PS Target Courant=0.9
PS Time Slices= 1
PS Iterate With 2D=0
PS Project Initial WSE from DS=-1
PS Ramp Up Initial WSE from US=-1
PS Cores=0
UNET D1D2 MaxIter= 0
UNET D1D2 ZTol=0.01
UNET D1D2 QTol=0.1
UNET D1D2 MinQTol=1
Write IC File= 0
Write IC File at Fixed DateTime=0
Write IC File at Sim End=0
Echo Input=False
Echo Parameters=False
Echo Output=False
Write Detailed= 0
HDF Write Warmup=0
HDF Write Time Slices=0
HDF Flush=0
HDF Compression= 1
HDF Chunk Size= 1
HDF Spatial Parts= 1
HDF Use Max Rows=0
HDF Fixed Rows= 1
Calibration Method= 0
Calibration Iterations= 20
Calibration Max Change=0.05
Calibration Tolerance=0.2
Calibration Maximum=1.5
Calibration Minimum=0.5
Calibration Optimization Method= 1
WQ AD Non Conservative
WQ ULTIMATE=-1
WQ Max Comp Step=1HOUR
WQ Output Interval=15MIN
WQ Output Selected Increments= 0
WQ Create Restart=0
WQ Fixed Restart=0
WQ System Summary=0
WQ Write To DSS=0
Sorting and Armoring Iterations= 10
XS Update Threshold= 0.02
Bed Roughness Predictor= 0
Processes Affected by Predictor=Sediment Only
Hydraulics Update Threshold= 0.02
Energy Slope Method= 1
Volume Change Method= 1
Sediment Retention Method= 0
Sediment TS Multiplier= 1
Warm Up Method= 0
XS Weighting Method= 0
Number of US Weighted Cross Sections= 1
Number of DS Weighted Cross Sections= 1
Upstream XS Weight=0
Main XS Weight=1
Downstream XS Weight=0
Number of DS XS's Weighted with US Boundary= 1
Upstream Boundary Weight= 1
Weight of XSs Associated with US Boundary= 0
Number of US XS's Weighted with DS Boundary= 1
Downstream Boundary Weight= 0.5
Weight of XSs Associated with DS Boundary= 0.5
Percentile Method= 0
Sediment Output Level= 3
Mass or Volume Output= 0
Output Increment Type= 1
Profile and TS Output Increment= 1
Transport Output Increment 1
XS Output Flag= 0
XS Output Increment= 10
Read HDF5 Sediment Hotstart= 0
Sediment Hotstart Type= 0
Write Gradation File= 0
Read Gradation Hotstart= 0
Write HDF5 File= 1
Write Binary Output= 1
Write DSS Sediment File= 0
DSS Sediment Output Type= 1
SV Curve= 0
Specific Gage Flag= 0
Subcell Erosion Methods= 0
Subcell Deposition Methods= 0
Advection Scheme= 1
Matrix Solver= 0
Implicit Weighting Factor= 1
Maximum Outer Loop Convergence Iterations= 5
Convergence Maximum Absolute= 0.001
Convergence RMSE= 0.0001
Grain Fractions Max Abs Error= 0.001
Max Subgrid Regions= 1
Max Subgrid Length Scale= 3.402823E+38
Initial Layer Thickness= 3
Min Layer Thickness= 0.1
Max Layer Thickness= 6
Number of Layers= 5

--- TurkeyRn.f01 (steady flow) ---

Flow Title=Flow
Program Version=6.60
Number of Profiles= 1
Profile Names=P100yr
River Rch & RM=TurkeyRn,Main,25316
     854
River Rch & RM=TurkeyRn,Main,23265
    1050
River Rch & RM=TurkeyRn,Main,19573
    1340
River Rch & RM=TurkeyRn,Main,18000
    1540
River Rch & RM=TurkeyRn,Main,15126
    1720
River Rch & RM=TurkeyRn,Main,10730
    2060
River Rch & RM=TurkeyRn,Main,6000
    2330
Boundary for River Rch & Prof#=TurkeyRn,Main            , 1
Up Type= 0
Dn Type= 3
Dn Slope=0.003387
DSS Import GetInterval= 0
DSS Import GetPeak= 0
DSS Import FillOption= 0

--- TurkeyRn.g01 (geometry) ---

Geom Title=Geometry
Program Version=6.60

River Reach=TurkeyRn        ,Main
Reach XY= 30
      1679995.59      548958.656     1678383.518      547769.237
     1677972.849      547126.556     1677306.807      546902.578
     1676838.066      546250.933     1676084.045       545782.54
     1675832.421      545897.301     1674883.207      544896.339
     1674481.303      544720.732     1674292.337      544124.717
     1673382.838      542943.342     1673326.313      542378.613
     1672727.278      541732.786     1672745.022      541321.863
     1672194.307      541033.548     1672208.926      540207.635
     1672067.139      539890.547     1671636.866      539407.263
     1671241.054      539438.114     1670785.758      537643.544
     1670174.079      537547.298     1669969.754      537782.271
     1669328.134      537376.125     1667831.474      537425.361
     1667412.063      537091.641     1667343.565       536779.05
     1666490.256      536221.115     1664979.349      536494.775
     1664347.665       536192.73     1663902.526      535393.961

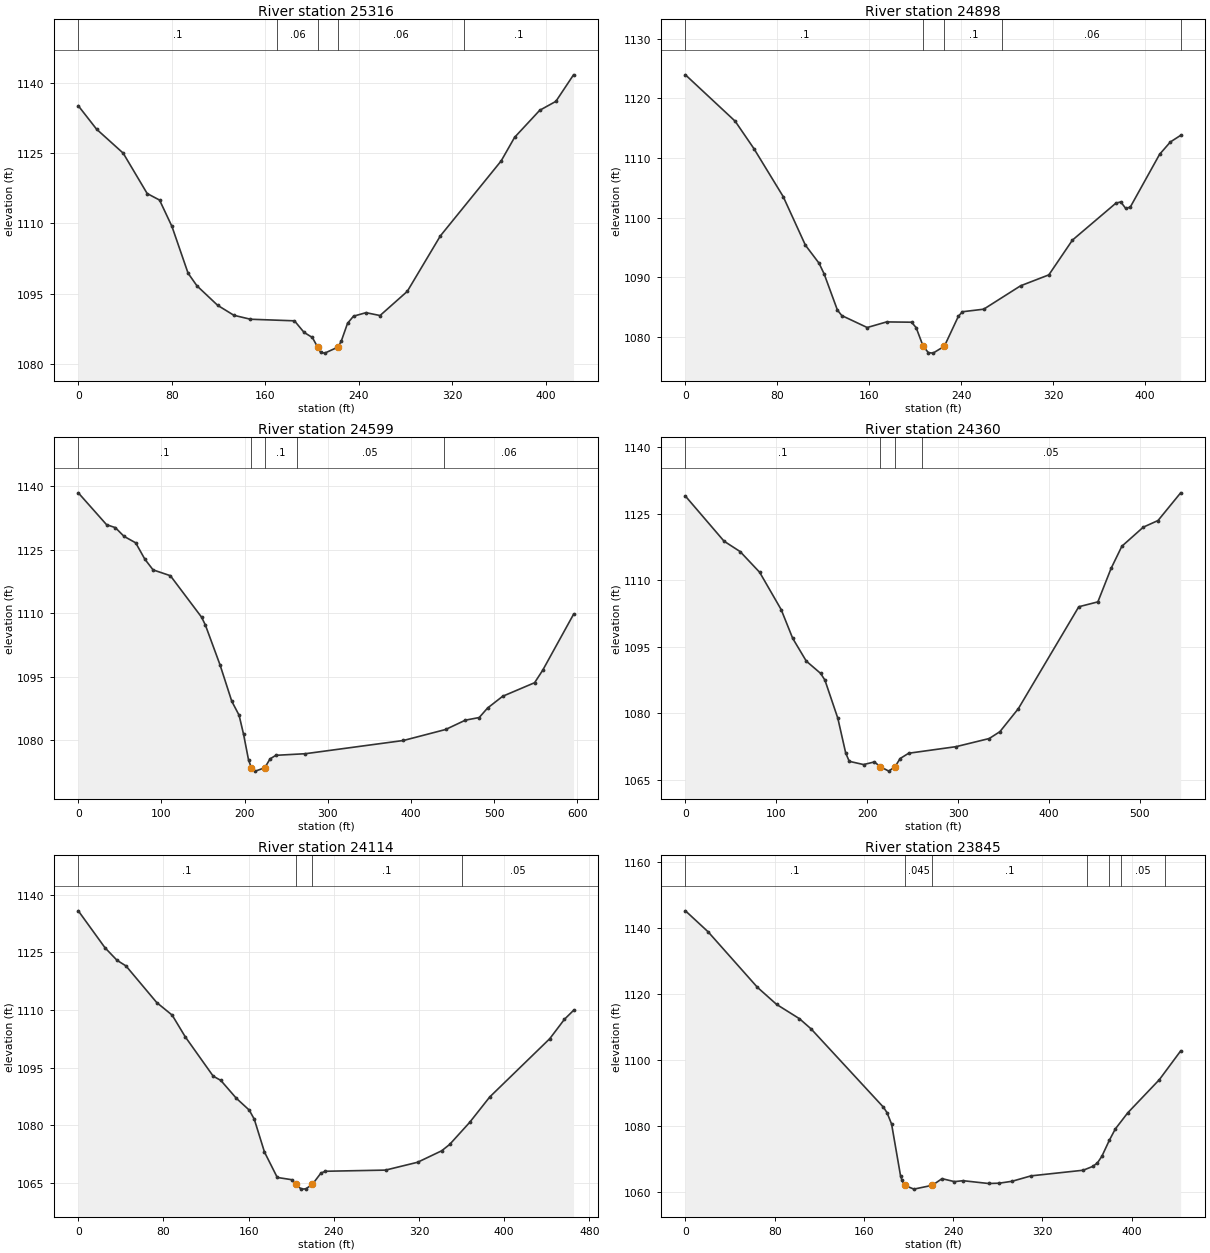
Type RM Length L Ch R = 1 ,25316   ,416.3,417.7,417.3
XS GIS Cut Line= 2
1680059.57616245548757.3085143821679902.88864947549150.877936766
#Sta/Elev= 30
       0 1135.14    15.6 1130.15    38.4 1125.02    58.9  1116.4    69.5    1115
    80.1 1109.37    93.9 1099.38   101.5 1096.68   119.2 1092.52   133.1 1090.39
   147.2 1089.55   184.9 1089.21   193.1 1086.74   200.2 1085.65  204.771083.578
   207.3 1082.46   210.8 1082.31  221.931083.578   224.9 1084.84   230.3 1088.68
   235.4  1090.2   246.1 1090.95   258.1 1090.34   281.4  1095.5   309.7 1107.35
   361.7 1123.36   373.2  1128.4   394.7 1134.18   408.5 1136.08   423.6 1141.75
#Mann= 5 ,-1,0
       0      .1       0     170     .06       0  204.77    .045       0
  221.93     .06       0     330      .1       0
Bank Sta=204.77,221.93
XS Rating Curve= 0 ,0
Exp/Cntr(USF)=0,0
Exp/Cntr=0.3,0.1

Type RM Length L Ch R = 1 ,24898   ,296.9,299.7,296.1
XS GIS Cut Line= 6
1679763.16330734548574.1698814181679697.89211242548636.232421339
1679655.25013734548698.7198291721679610.17706476548788.225555673
1679564.28312768548849.214606926 1679508.4558115548918.211844251
#Sta/Elev= 30
       0 1123.95    43.3 1116.18    59.6 1111.59    85.1 1103.55   104.4 1095.42
   116.3 1092.39   120.7 1090.61   132.3 1084.53   136.1 1083.62   158.2 1081.62
   175.1 1082.56   196.8 1082.51   200.8  1081.6   206.91078.482   211.4 1077.42
   215.5 1077.33  225.361078.483   237.5 1083.48     241 1084.26   259.6 1084.69
   291.7 1088.61   316.3 1090.44   336.8 1096.26   374.7 1102.46   378.9 1102.66
   383.1 1101.59   387.1 1101.77   412.7 1110.64   422.1 1112.71     431 1113.81
#Mann= 5 ,-1,0
       0      .1       0   206.9    .045       0  225.36      .1       0
  275.93     .06       0  431.01     .05       0
Bank Sta=206.9,225.36
XS Rating Curve= 0 ,0
Exp/Cntr(USF)=0,0
Exp/Cntr=0.3,0.1

Type RM Length L Ch R = 1 ,24599   ,236.5,238.7,239.6
XS GIS Cut Line= 6
1679525.14278601548327.441700339 1679494.8006551548409.577362835
1679468.96868576548480.0408045951679431.73221168548572.850986421
1679386.37777038548691.0661295671679421.14644616548894.238556082
#Sta/Elev= 30
       0 1138.48      34 1130.94    44.5 1130.25      55 1128.18      69 1126.65
      80 1122.78    89.9 1120.25   110.7 1118.87   148.2 1109.06   152.8 1107.19
   170.4 1097.77   184.5 1089.17   193.3 1085.86   198.7 1081.34   204.7 1075.25
  208.14 1073.42   212.8 1072.63  224.181073.419   230.5 1075.52   237.5 1076.37
   272.9 1076.75   390.9 1079.88   441.6 1082.48   465.4 1084.69     482 1085.31
     492 1087.55   510.2 1090.34   548.6 1093.55   558.3 1096.49   595.4 1109.73
#Mann= 5 ,-1,0
       0      .1       0  208.14    .045       0  224.18      .1       0
  262.61     .05       0  439.23     .06       0
Bank Sta=208.14,224.18
XS Rating Curve= 0 ,0
Exp/Cntr(USF)=0,0
Exp/Cntr=0.3,0.1

Type RM Length L Ch R = 1 ,24360   ,246.3,246.3,245.3
XS GIS Cut Line= 2
1679363.03484251548242.1882619261679060.17312414 548695.30200948
#Sta/Elev= 30
       0 1128.93    42.5 1118.78    60.2 1116.44    81.7 1111.77   105.4 1103.36
     118 1096.92     133 1091.77   148.8    1089   153.5 1087.49   167.7 1078.91
   176.4 1071.05   180.3  1069.2     196 1068.47     208 1069.06  214.181068.015
   223.8 1066.99  230.731068.015   236.3 1069.83   245.7 1071.02   297.8  1072.5
   334.3 1074.33   346.1 1075.88   366.4 1081.07   432.9 1104.01   453.9 1105.11
   468.4 1112.63   480.3 1117.64   503.9 1121.94   520.1 1123.43     545 1129.67
#Mann= 4 ,-1,0
       0      .1       0  214.18    .045       0  230.73      .1       0
     260     .05       0
Bank Sta=214.18,230.73
XS Rating Curve= 0 ,0
Exp/Cntr(USF)=0,0
Exp/Cntr=0.3,0.1

Type RM Length L Ch R = 1 ,24114   ,266.3,269,263.6
XS GIS Cut Line= 2
1679155.50212109548094.6898692551678927.40133596548500.087104592
#Sta/Elev= 30
       0 1135.83    25.1 1126.21    36.4 1122.95    44.8 1121.49    73.7 1111.95
    88.2 1108.68   100.4 1103.07   126.7 1092.81   133.9 1091.69   148.4 1087.06
   160.6 1083.96   165.3  1081.6   174.9 1073.04   186.9 1066.44   200.3 1065.86
  204.411064.626   209.5  1063.4   213.7 1063.47  219.821064.625   227.9 1067.57
   232.1 1068.05   288.6 1068.35   318.7 1070.39   341.3 1073.37   348.8 1075.02
   367.6 1080.76   386.5 1087.39   442.9 1102.56   456.7 1107.61   465.2 1109.92
#Mann= 4 ,-1,0
       0      .1       0  204.41    .045       0  219.82      .1       0
     360     .05       0
Bank Sta=204.41,219.82
XS Rating Curve= 0 ,0
Exp/Cntr(USF)=0,0
Exp/Cntr=0.3,0.1

Type RM Length L Ch R = 1 ,23845   ,144.3,145.2,144.6
XS GIS Cut Line= 2
1679015.72352565547935.8989239041678760.33521708548298.994475654
#Sta/Elev= 30
       0  1145.3    20.3 1138.94    64.5 1122.07    81.7 1116.88   102.2 1112.53
   112.6 1109.45   177.5 1085.64   180.7 1083.99   184.8 1080.52   192.8 1064.84
     194 1063.56  196.381061.931   204.8 1060.76  221.351061.932     230 1063.94
   241.1 1063.04   248.9 1063.32   271.7 1062.47   281.1 1062.56   292.7 1063.14
   309.8 1064.79   356.5  1066.5   365.2 1067.67   369.3 1068.73   373.3 1070.75
     380 1075.62   385.3 1079.02   396.5 1083.95   424.8 1094.01   443.9 1102.74
#Mann= 7 ,-1,0
       0      .1       0  196.38    .045       0  221.35      .1       0
     360     .05       0     380      .1       0     390     .05       0
     430      .1       0
Bank Sta=196.38,221.35
XS Rating Curve= 0 ,0
Exp/Cntr(USF)=0,0
Exp/Cntr=0.3,0.1

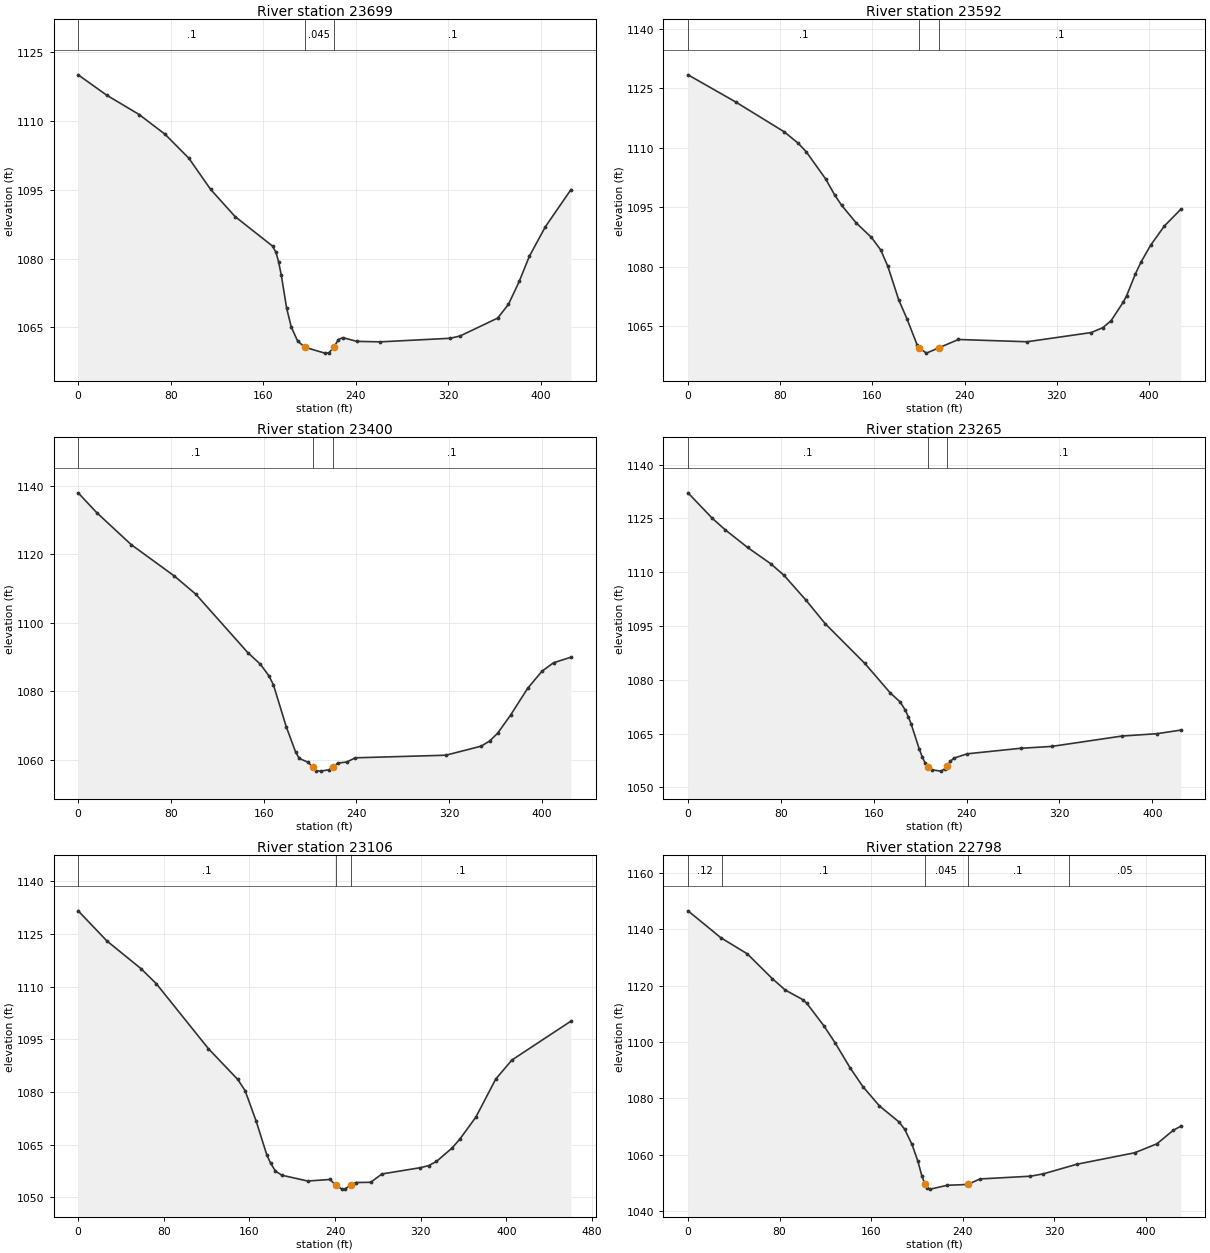
Type RM Length L Ch R = 1 ,23699   ,106.7,107.1,106.3
XS GIS Cut Line= 6
1678903.26870167547857.8409335021678848.42202659547926.241715342
1678805.16948843 547987.512590171678746.68436918548068.635459423
1678697.74745917548125.9125758411678640.00249593548192.220842168
#Sta/Elev= 30
       0 1120.11    24.6 1115.68    52.7 1111.45    75.1 1107.14    95.7  1101.9
   114.4 1095.14   135.6 1089.19     168 1082.74   170.9 1081.41   173.2 1079.36
   175.6 1076.35   180.2 1069.17   184.2 1065.07   189.7 1062.02  196.031060.666
   213.2 1059.39   216.6 1059.45  220.991060.666   224.9 1062.35   228.7 1062.77
   240.8 1061.96   261.1 1061.85   321.4 1062.63     330 1063.12   362.6 1067.04
   371.9 1070.03   381.2 1075.03     390 1080.54   403.9    1087   425.9 1095.06
#Mann= 3 ,-1,0
       0      .1       0  196.03    .045       0  220.99      .1       0
Bank Sta=196.03,220.99
XS Rating Curve= 0 ,0
Exp/Cntr(USF)=0,0
Exp/Cntr=0.3,0.1

Type RM Length L Ch R = 1 ,23592   ,192.9,192.3,190.9
XS GIS Cut Line= 2
1678809.19211089547791.5490103651678568.23879367548144.651106561
#Sta/Elev= 30
       0 1128.43    41.2 1121.61    83.6 1114.03    95.6 1111.18   102.6 1109.01
   119.4 1102.18   127.3  1098.1   133.2 1095.55     146 1091.06   159.1 1087.43
   167.1 1084.31   173.4  1080.1   182.9  1071.6   189.9 1066.95   198.8 1060.31
  200.291059.642   206.8 1058.25  218.021059.644   234.6 1061.69   294.2 1061.12
   349.8 1063.44   359.9 1064.68     367 1066.42   377.6 1071.11   380.6 1072.78
   388.2 1078.28   392.9 1081.16   401.4 1085.49   413.3 1090.32   427.5 1094.52
#Mann= 3 ,-1,0
       0      .1       0  200.29    .045       0  218.02      .1       0
Bank Sta=200.29,218.02
XS Rating Curve= 0 ,0
Exp/Cntr(USF)=0,0
Exp/Cntr=0.3,0.1

Type RM Length L Ch R = 1 ,23400   ,134.1,134.8,134.3
XS GIS Cut Line= 6
1678624.40213342547682.5604441761678583.22537851547759.766326502
1678547.93148585547825.943031415  1678500.873181547914.178419262
1678465.57928833547980.3551241761678424.40351768548057.561334595
#Sta/Elev= 30
       0 1137.88    15.9 1132.14    45.7 1122.79    82.8 1113.67   101.4 1108.35
   146.3  1091.3   157.2  1087.9   164.6 1084.48   168.4 1081.92   179.5 1069.66
   187.5 1062.36   190.7 1060.45   198.1 1059.36  202.271058.004   205.5 1056.85
   209.3 1056.75   216.6 1057.16  219.581058.005   224.1 1059.11   231.6  1059.4
     239 1060.63   317.1 1061.39   347.6 1064.03   354.9 1065.54   361.7 1067.76
   372.9 1073.06   387.7  1080.9   400.1  1085.9     410 1088.34     425 1089.96
#Mann= 3 ,-1,0
       0      .1       0  202.27    .045       0  219.58      .1       0
Bank Sta=202.27,219.58
XS Rating Curve= 0 ,0
Exp/Cntr(USF)=0,0
Exp/Cntr=0.3,0.1

Type RM Length L Ch R = 1 ,23265   ,153.1,159.4,163.7
XS GIS Cut Line= 3
1678552.59564883547626.4488783151678427.16910671547773.082806783
1678318.10254835547977.279641054
#Sta/Elev= 30
       0 1132.13      21    1125    31.9 1121.86    51.3  1116.9    71.1 1112.39
    82.7 1109.13   101.8 1102.13   118.2 1095.64   152.3 1084.57   174.3 1076.31
   182.8 1073.81   187.3 1071.47   189.8 1069.67   192.1  1067.8   199.2 1060.69
   201.8 1058.48   204.2 1056.86   206.5 1055.75   210.4 1054.88   217.8 1054.53
   221.1 1055.14   222.9 1055.88     226 1057.25     229 1058.14   240.5 1059.36
   286.6  1060.9   313.3 1061.42     374 1064.32   403.8 1064.96   424.5 1065.97
#Mann= 3 ,-1,0
       0      .1       0   206.5    .045       0   222.9      .1       0
Bank Sta=206.5,222.9
XS Rating Curve= 0 ,0
Exp/Cntr(USF)=0,0
Exp/Cntr=0.3,0.1

Type RM Length L Ch R = 1 ,23106   ,305.4,307.9,285.9
XS GIS Cut Line= 6
1678537.49449883547611.1606525931678449.37558059547647.712416753
1678366.74221568547671.8206362581678256.79296051 547708.84254384
1678190.11330384547743.4684588461678112.90840575547785.035961002
#Sta/Elev= 30
       0 1131.61    26.9 1123.01    58.8 1115.11    73.1  1110.8   121.7 1092.32
   149.1 1083.55   155.9 1080.39   166.2 1071.75   176.2 1062.08   179.8 1059.67
   184.3 1057.46   190.2 1056.28   214.4 1054.62   235.2 1055.06  240.591053.449
   246.4 1052.31   249.1 1052.35  254.671053.449   259.4 1054.19   273.3 1054.26
   283.7 1056.63   319.7 1058.42   327.4 1059.01   334.7  1060.2   349.3 1064.03
   356.7 1066.63   371.5 1072.83   390.1  1083.7   405.2  1089.1   460.3 1100.18
#Mann= 3 ,-1,0
       0      .1       0  240.59    .045       0  254.67      .1       0
Bank Sta=240.59,254.67
XS Rating Curve= 0 ,0
Exp/Cntr(USF)=0,0
Exp/Cntr=0.3,0.1

Type RM Length L Ch R = 1 ,22798   ,217.4,217.8,205.4
XS GIS Cut Line= 6
1678432.68729375547339.9751713421678356.30490059547382.659469172
1678290.83390293547419.2463382481678201.46137826547464.309240252
1678132.88835268547497.0821405951678056.88653618547548.558743671
#Sta/Elev= 30
       0 1146.61    28.6 1137.07    51.8 1131.32    73.7 1122.49      85 1118.45
   100.1  1115.1   103.8 1113.74   118.8 1105.69   128.6 1099.63   141.4 1090.95
   152.7 1084.19   167.2  1077.3   184.3 1071.61   189.2 1069.03   195.6 1063.65
   200.7 1057.76   204.3 1052.36  207.061049.406   208.7  1048.2   211.7 1047.75
   226.4 1049.12  244.191049.402   255.1 1051.37   299.1 1052.34   310.4 1053.18
   339.6 1056.59   390.2 1060.67   409.6 1063.86   423.8 1068.65   430.4  1070.1
#Mann= 5 ,-1,0
       0     .12       0      30      .1       0  207.06    .045       0
  244.19      .1       0  332.59     .05       0
Bank Sta=207.06,244.19
XS Rating Curve= 0 ,0
Exp/Cntr(USF)=0,0
Exp/Cntr=0.3,0.1

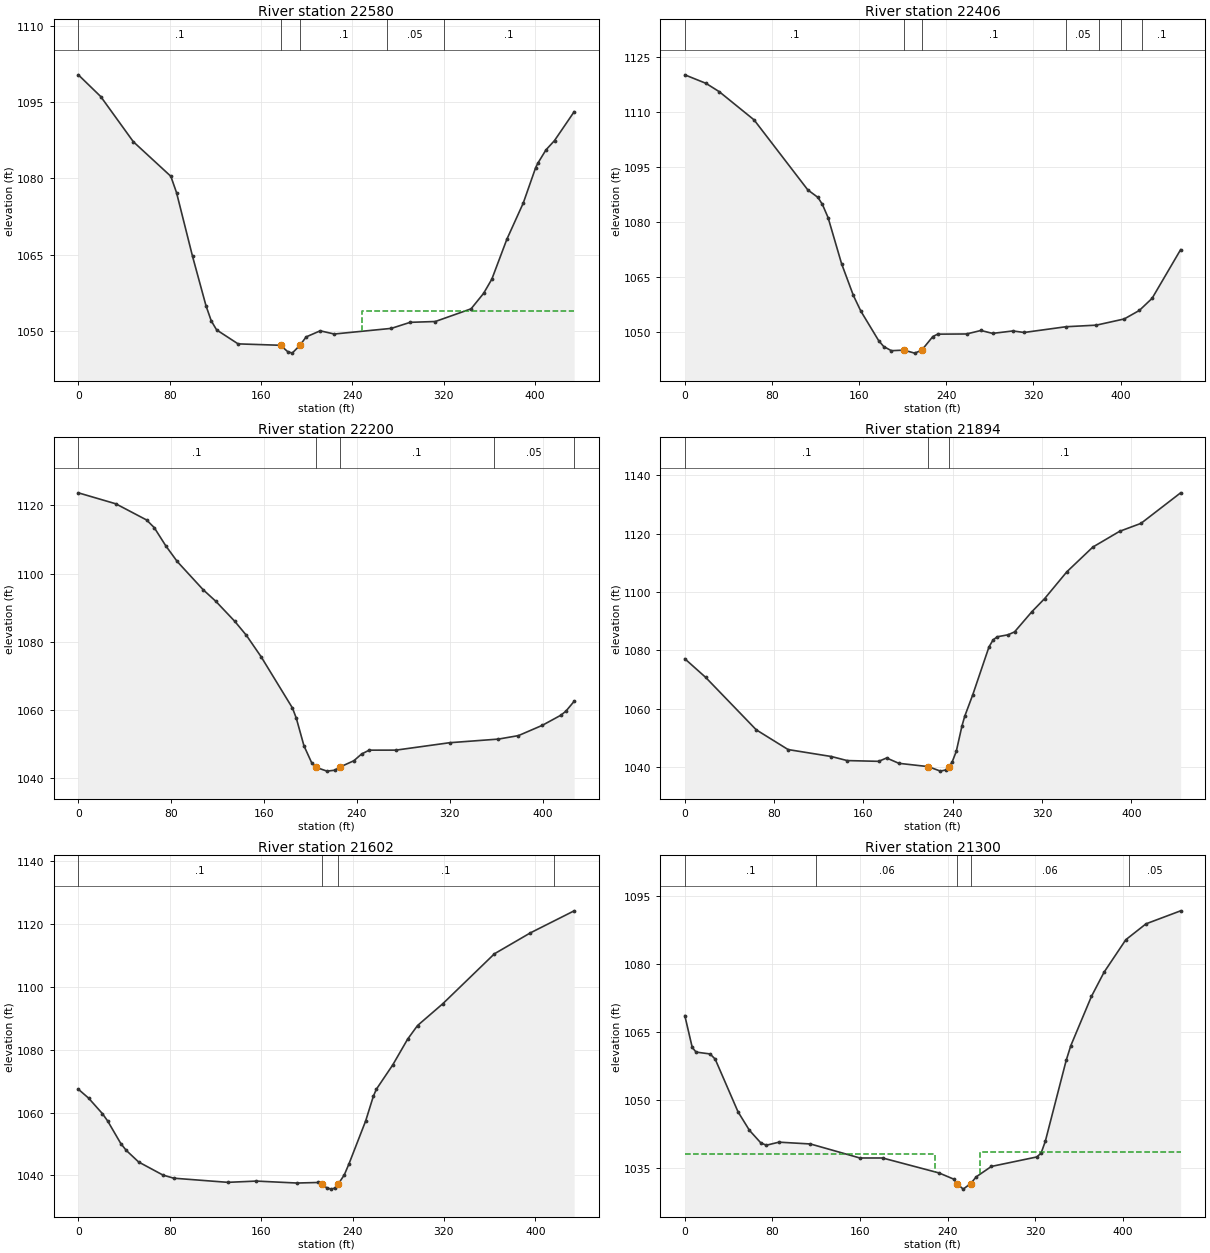
Type RM Length L Ch R = 1 ,22580   ,175.7,174.4,173
XS GIS Cut Line= 2
1678236.42397215547195.0905127571677887.99651941547454.239600752
#Sta/Elev= 30
       0 1100.36    19.6 1096.09    48.2 1087.19      81  1080.4      86 1077.18
     100 1064.66   111.8 1054.93   116.4 1051.96   121.1 1050.18   139.9 1047.43
  177.091047.154   183.2 1045.93   187.3 1045.61  194.061047.152   199.5  1048.8
   211.8    1050   224.1 1049.37   274.1 1050.48   290.6 1051.67   312.6 1051.83
   343.9 1054.32   354.9 1057.37   362.1 1060.16   375.3 1068.03   389.6 1075.12
   400.5 1082.11   402.5 1083.01   409.5 1085.59     417 1087.43   434.2  1093.1
#Mann= 5 ,-1,0
       0      .1       0  177.09    .045       0  194.06      .1       0
     270     .05       0     320      .1       0
#XS Ineff= 2 , 0
                          248.74         1053.98
Permanent Ineff=
       F       F
Bank Sta=177.09,194.06
XS Rating Curve= 0 ,0
Exp/Cntr(USF)=0,0
Exp/Cntr=0.3,0.1

Type RM Length L Ch R = 1 ,22406   ,210.3,205.7,200
XS GIS Cut Line= 2
1678135.18905305547012.0594772511677831.24250103547350.715082634
#Sta/Elev= 30
       0 1120.06    19.4 1117.75    31.6 1115.48    63.6  1107.8   112.9 1088.76
   122.2 1086.72   126.3 1084.81   131.5 1081.24   143.9 1068.69   154.7 1060.07
   161.6 1055.78   177.9 1047.78   182.6 1046.15   189.6 1045.02   201.2 1045.18
   210.9 1044.36  217.35 1045.12   227.7 1048.88   232.1 1049.52   258.6 1049.57
   271.8 1050.52   282.5 1049.73   301.1 1050.39   311.5 1049.98   349.9 1051.54
   377.7 1051.97   403.3 1053.65   417.2 1055.97   428.9 1059.26   455.1 1072.51
#Mann= 7 ,-1,0
       0      .1       0   201.2    .045       0  217.35      .1       0
     350     .05       0     380      .1       0     400     .05       0
     420      .1       0
Bank Sta=201.2,217.35
XS Rating Curve= 0 ,0
Exp/Cntr(USF)=0,0
Exp/Cntr=0.3,0.1

Type RM Length L Ch R = 1 ,22200   ,299.9,305.7,305.9
XS GIS Cut Line= 6
1677849.74620242546877.1591678411677838.62056851546963.948692426
1677829.08417025547038.3399478351677816.36962876547137.528725833
1677809.90737134547212.5006887611677797.44446975547301.074002415
#Sta/Elev= 30
       0 1123.67    32.3 1120.45    58.8 1115.71    65.4 1113.47    75.3 1108.15
    85.2 1103.53   107.6 1095.23   118.3 1091.91   134.8 1085.98   144.8 1081.87
   157.5 1075.58   184.5 1060.55   187.8 1057.57   194.4 1049.47     201 1044.53
  204.431043.196   214.2 1042.04   220.8  1042.3  225.161043.195   237.4 1045.09
     244 1047.05   250.6 1048.19   273.7  1048.2   319.8 1050.37     362 1051.44
   379.2 1052.46   399.8 1055.48   415.8 1058.45   420.1 1059.63   427.2 1062.53
#Mann= 5 ,-1,0
       0      .1       0  204.43    .045       0  225.16      .1       0
  357.75     .05       0   427.2      .1       0
Bank Sta=204.43,225.16
XS Rating Curve= 0 ,0
Exp/Cntr(USF)=0,0
Exp/Cntr=0.3,0.1

Type RM Length L Ch R = 1 ,21894   ,287.7,292.7,294.8
XS GIS Cut Line= 6
1677618.57015559546853.5686638361677581.68899576546940.300773844
1677551.52993535547017.6519970891677504.91355875547110.848004922
1677464.25484742547173.8708447521677416.81990293547247.397600591
#Sta/Elev= 30
       0 1077.08    18.6 1070.72      64 1052.69    92.5 1045.92   131.3 1043.53
   145.4 1042.14   173.6 1041.88   180.7 1043.03   191.7  1041.2  218.011040.069
   228.9 1038.52   233.5 1038.92  236.64 1040.07   239.4 1041.64   243.1  1045.3
   248.2 1054.02   250.6 1057.27   257.8 1064.66   272.4 1081.15   276.1 1083.56
   279.8 1084.62   289.5  1085.3   295.3  1086.3   310.9 1093.26   322.3 1097.75
   342.1 1106.91   365.4  1115.4   389.4 1120.81   408.5 1123.53     444 1134.01
#Mann= 3 ,-1,0
       0      .1       0  218.01    .045       0  236.64      .1       0
Bank Sta=218.01,236.64
XS Rating Curve= 0 ,0
Exp/Cntr(USF)=0,0
Exp/Cntr=0.3,0.1

Type RM Length L Ch R = 1 ,21602   ,296.4,301.7,302.2
XS GIS Cut Line= 6
1677466.25615576546748.5357374251677397.74316943546809.244277418
1677337.07006243546860.0722597541677258.90486443546923.722394928
1677202.36856018546973.0008396661677136.40871835547030.493506834
#Sta/Elev= 30
       0 1067.43       9  1064.6      21 1059.69    25.6 1057.37    37.2 1050.14
    41.9 1047.99    52.8 1044.28    74.1 1040.12    83.5 1039.13   130.8 1037.81
   155.9 1038.21   191.3 1037.59   209.5 1037.76  213.17 1037.27   217.3 1036.12
   221.2 1035.65   224.3 1035.95   227.51037.269   232.8 1040.18     237 1043.79
   251.5 1057.34   258.2 1065.16   260.8 1067.39   275.2 1075.16   288.2 1083.34
   296.9 1087.69     319 1094.62   364.2 1110.51   395.7 1117.17     434 1124.18
#Mann= 4 ,-1,0
       0      .1       0  213.17    .045       0   227.5      .1       0
  416.49     .05       0
Bank Sta=213.17,227.5
XS Rating Curve= 0 ,0
Exp/Cntr(USF)=0,0
Exp/Cntr=0.3,0.1

Type RM Length L Ch R = 1 ,21300   ,89.2,87.7,87.1
XS GIS Cut Line= 5
1677380.63584094546574.4223762781677257.60565442546618.144593999
1677186.30264743546641.5523555871677090.24640909546669.359386593
1677014.47819092546795.183941086
#Sta/Elev= 30
       0 1068.63     6.8 1061.62    10.3  1060.6    23.1 1060.19    27.7 1059.07
    48.6 1047.45      59 1043.39    69.5  1040.6    74.5 1040.12    85.9 1040.79
   114.7 1040.39   159.8 1037.31   180.5 1037.31     232 1034.02   245.6 1032.64
  248.34 1031.69   254.1 1030.46  260.88 1031.69   266.1 1033.19   279.8 1035.45
   321.3 1037.54   325.2  1038.4     329 1040.97   348.1 1058.81   352.3 1062.03
   371.1 1072.84   382.6 1078.16   402.5 1085.32   420.9 1088.81   452.5 1091.67
#Mann= 5 ,-1,0
       0      .1       0     120     .06       0  248.34    .045       0
  260.88     .06       0  405.62     .05       0
#XS Ineff= 2 , 0
          228.52 1038.21  269.31          1038.6
Permanent Ineff=
       F       F
Bank Sta=248.34,260.88
XS Rating Curve= 0 ,0
Exp/Cntr(USF)=0,0
Exp/Cntr=0.3,0.1

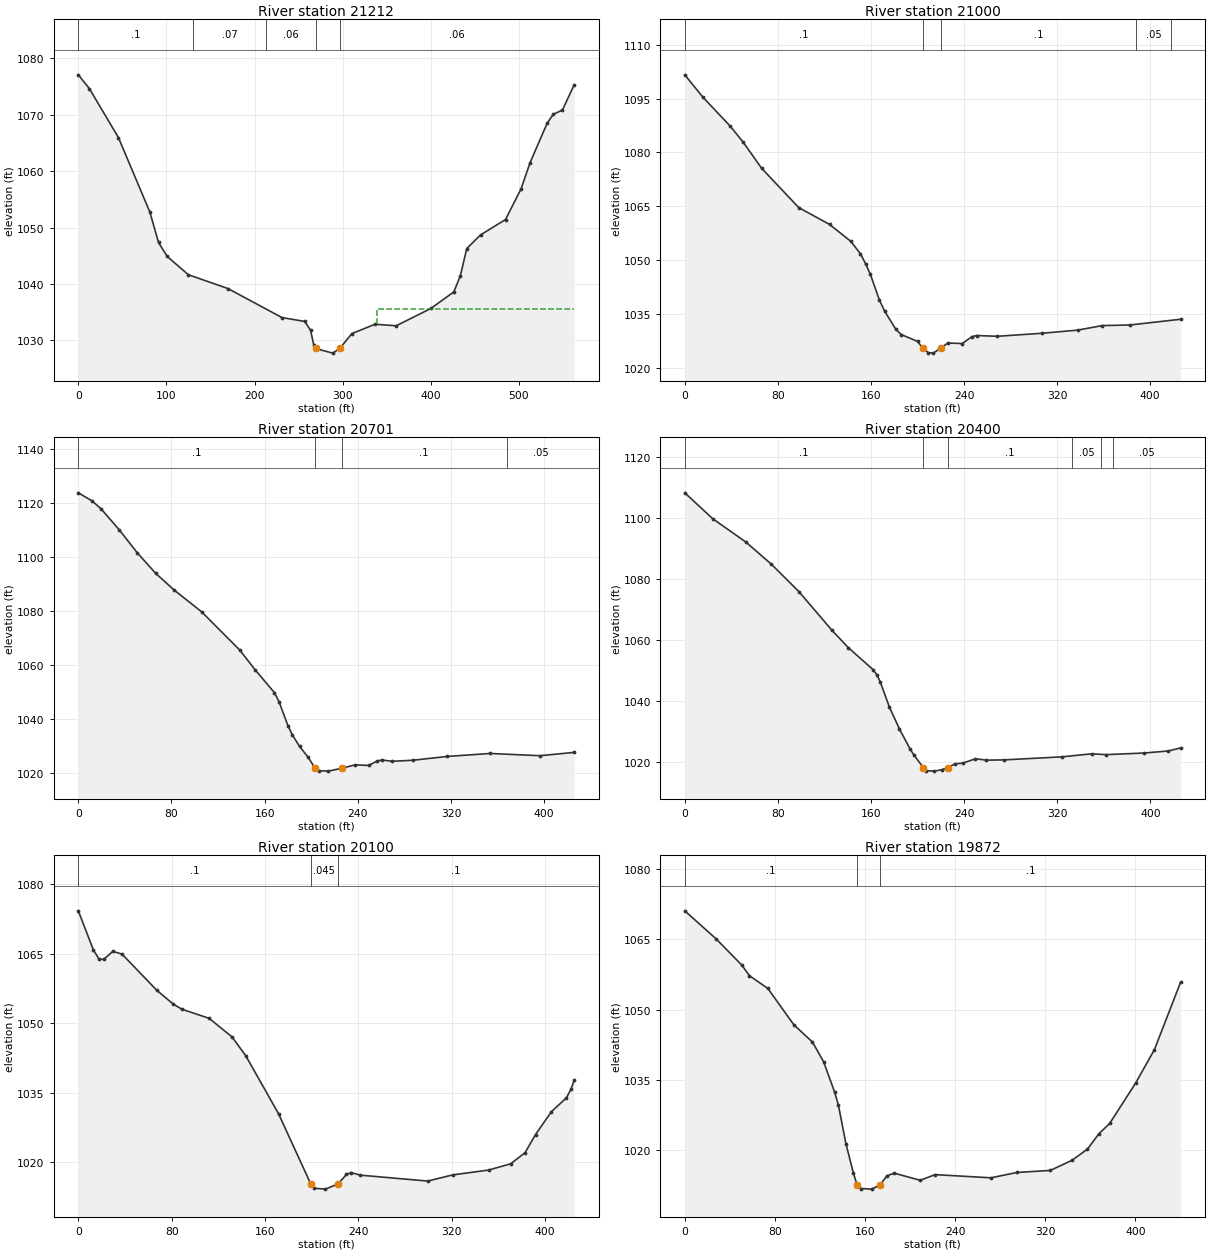
Type RM Length L Ch R = 1 ,21212   ,215,212.6,209.4
XS GIS Cut Line= 4
1677335.87546608546418.5430645761677222.28200116546520.694668148
1677008.86803906546618.756810979  1676930.632301546775.425364091
#Sta/Elev= 30
       0  1077.1    12.5 1074.67    45.5 1065.98    81.2 1052.76      91 1047.37
   100.9 1044.89   124.9 1041.65   169.7 1039.21   231.1 1034.06   256.9 1033.37
   263.6  1031.8   267.2 1029.24  269.241028.571   288.8 1027.75  296.731028.571
   310.5 1031.22   336.8 1032.87   360.8  1032.6   400.3 1035.68   426.2 1038.61
   433.6 1041.44   440.9  1046.3   456.5 1048.71   484.9 1051.44   502.5 1056.87
   512.8 1061.54   532.3 1068.57   539.2  1070.1   549.5 1070.87   562.8 1075.32
#Mann= 5 ,-1,0
       0      .1       0     130     .07       0  212.77     .06       0
  269.24    .045       0  296.73     .06       0
#XS Ineff= 2 , 0
                          339.21          1035.5
Permanent Ineff=
       F       F
Bank Sta=269.24,296.73
XS Rating Curve= 0 ,0
Exp/Cntr(USF)=0,0
Exp/Cntr=0.3,0.1

Type RM Length L Ch R = 1 ,21000   ,301,298.3,294.1
XS GIS Cut Line= 6
1677154.90441626546267.8398484291677086.22640401546322.057915837
1677027.35972384 546368.53059192 1676948.4474801546429.957962513
1676886.59261693546472.9142414181676812.86146517546521.580154583
#Sta/Elev= 30
       0 1101.61    15.5  1095.4    38.9 1087.38    50.3 1082.82    66.1 1075.57
    97.9 1064.67   124.4 1059.97   142.7 1055.26   150.9 1051.83   155.7 1048.83
   159.5 1046.07   167.3  1038.9   171.9 1035.75   181.4 1030.79     186 1029.32
   200.1  1027.4  204.491025.563   209.4 1024.25   213.5 1024.14  220.251025.564
     226 1026.95   238.5 1026.81   246.8 1028.72   250.9 1029.04   268.7 1028.83
   307.3 1029.67   337.8 1030.55   358.9 1031.81   382.5 1031.97   426.2 1033.57
#Mann= 5 ,-1,0
       0      .1       0  204.49    .045       0  220.25      .1       0
  387.81     .05       0  417.81      .1       0
Bank Sta=204.49,220.25
XS Rating Curve= 0 ,0
Exp/Cntr(USF)=0,0
Exp/Cntr=0.3,0.1

Type RM Length L Ch R = 1 ,20701   ,302.2,301.4,298.3
XS GIS Cut Line= 6
 1676882.6661156546023.5306257611676834.68524042546096.701739252
1676793.55868226546159.4197896721676741.04074268546244.563976333
1676705.68123335546311.0648275911676665.19246918 546389.14964518
#Sta/Elev= 30
       0 1123.86    11.6  1120.9    19.3 1118.04    35.1 1110.16    50.8 1101.52
    66.5 1093.98    82.2 1087.84   105.8 1079.76   138.6 1065.56   151.9 1058.18
   168.4 1049.76   172.3 1046.44     180 1037.52   183.8 1034.07     190 1029.78
   197.2 1025.87  203.391021.684     207  1020.8   214.7 1020.64   226.11021.683
   237.7 1022.97   249.4 1022.75   256.8 1024.43   260.9 1024.76   269.5 1024.29
     287 1024.67   316.7 1026.08   353.8 1027.19   396.5 1026.36   425.8 1027.59
#Mann= 4 ,-1,0
       0      .1       0  203.39    .045       0   226.1      .1       0
  367.85     .05       0
Bank Sta=203.39,226.1
XS Rating Curve= 0 ,0
Exp/Cntr(USF)=0,0
Exp/Cntr=0.3,0.1

Type RM Length L Ch R = 1 ,20400   ,297.6,300,301.9
XS GIS Cut Line= 6
1676591.97903292545846.6766487511676559.98434626545928.117102668
 1676532.5601885545997.9233935031676495.99464484546090.998338595
  1676467.015044546160.5395380851676434.43111968546242.515752092
#Sta/Elev= 30
       0 1108.21    24.2 1099.65    52.4 1092.09    74.5 1084.76    98.2 1075.75
   126.4 1063.15   140.5 1057.44   161.7 1050.26   165.2 1048.47   168.1 1046.07
   175.8 1037.97   184.5 1030.73   193.4 1024.34   196.9 1022.22  204.931018.106
   207.5 1017.08   214.5 1016.93   221.3 1017.43  225.931018.105   232.2 1019.32
     239 1019.55   249.8 1020.99   259.2 1020.53   274.6 1020.62   324.3 1021.62
   349.6  1022.6   362.3 1022.34   394.8 1022.87   415.3 1023.53   426.1 1024.53
#Mann= 6 ,-1,0
       0      .1       0  204.93    .045       0  225.93      .1       0
   332.5     .05       0  357.84      .1       0  367.84     .05       0
Bank Sta=204.93,225.93
XS Rating Curve= 0 ,0
Exp/Cntr(USF)=0,0
Exp/Cntr=0.3,0.1

Type RM Length L Ch R = 1 ,20100   ,232.9,228.4,223.3
XS GIS Cut Line= 6
1676376.47585501545716.4977752571676328.42214534 545789.62164475
1676287.23325133545852.2993409191676232.31505409545935.869383752
1676191.12616009545998.5470799211676143.07343468546071.671277508
#Sta/Elev= 30
       0 1074.28    12.8  1065.9    17.8 1063.81    21.8 1063.81    29.6 1065.53
    37.5 1064.92    67.3  1057.1    81.5  1054.1    88.9 1053.01   112.1 1051.06
   131.7 1047.05   143.5 1042.98   171.6 1030.45  199.231015.284   202.3 1014.35
   211.8 1014.16  222.611015.284   229.8 1017.32   233.8 1017.75   241.6 1017.18
   299.5  1015.9   320.8 1017.23   351.6 1018.28   370.6 1019.63   382.9 1022.03
   391.9 1025.96   405.5 1030.89   418.3 1033.86   422.2  1035.7     425 1037.63
#Mann= 3 ,-1,0
       0      .1       0  199.23    .045       0  222.61      .1       0
Bank Sta=199.23,222.61
XS Rating Curve= 0 ,0
Exp/Cntr(USF)=0,0
Exp/Cntr=0.3,0.1

Type RM Length L Ch R = 1 ,19872   ,288.4,298.8,298
XS GIS Cut Line= 2
1676087.42779741  545615.40551731676041.54834548546053.129726084
#Sta/Elev= 30
       0 1071.12    27.6 1065.17    50.7  1059.5    57.3 1057.27    73.7 1054.53
    96.8 1046.76   113.3 1043.08   123.2 1038.86   133.1  1032.3   136.4 1029.52
     143 1021.37   149.6  1015.1  152.821012.628   156.2 1011.77   166.1 1011.64
  173.651012.629   179.3 1014.48   185.9 1015.05     209 1013.53   222.2 1014.74
   271.7 1014.06   294.8  1015.2   324.5 1015.64   343.8 1017.82   357.4 1020.19
   367.3  1023.4   377.2  1025.7   400.3 1034.36   416.8 1041.43   440.1 1055.88
#Mann= 3 ,-1,0
       0      .1       0  152.82    .045       0  173.65      .1       0
Bank Sta=152.82,173.65
XS Rating Curve= 0 ,0
Exp/Cntr(USF)=0,0
Exp/Cntr=0.3,0.1

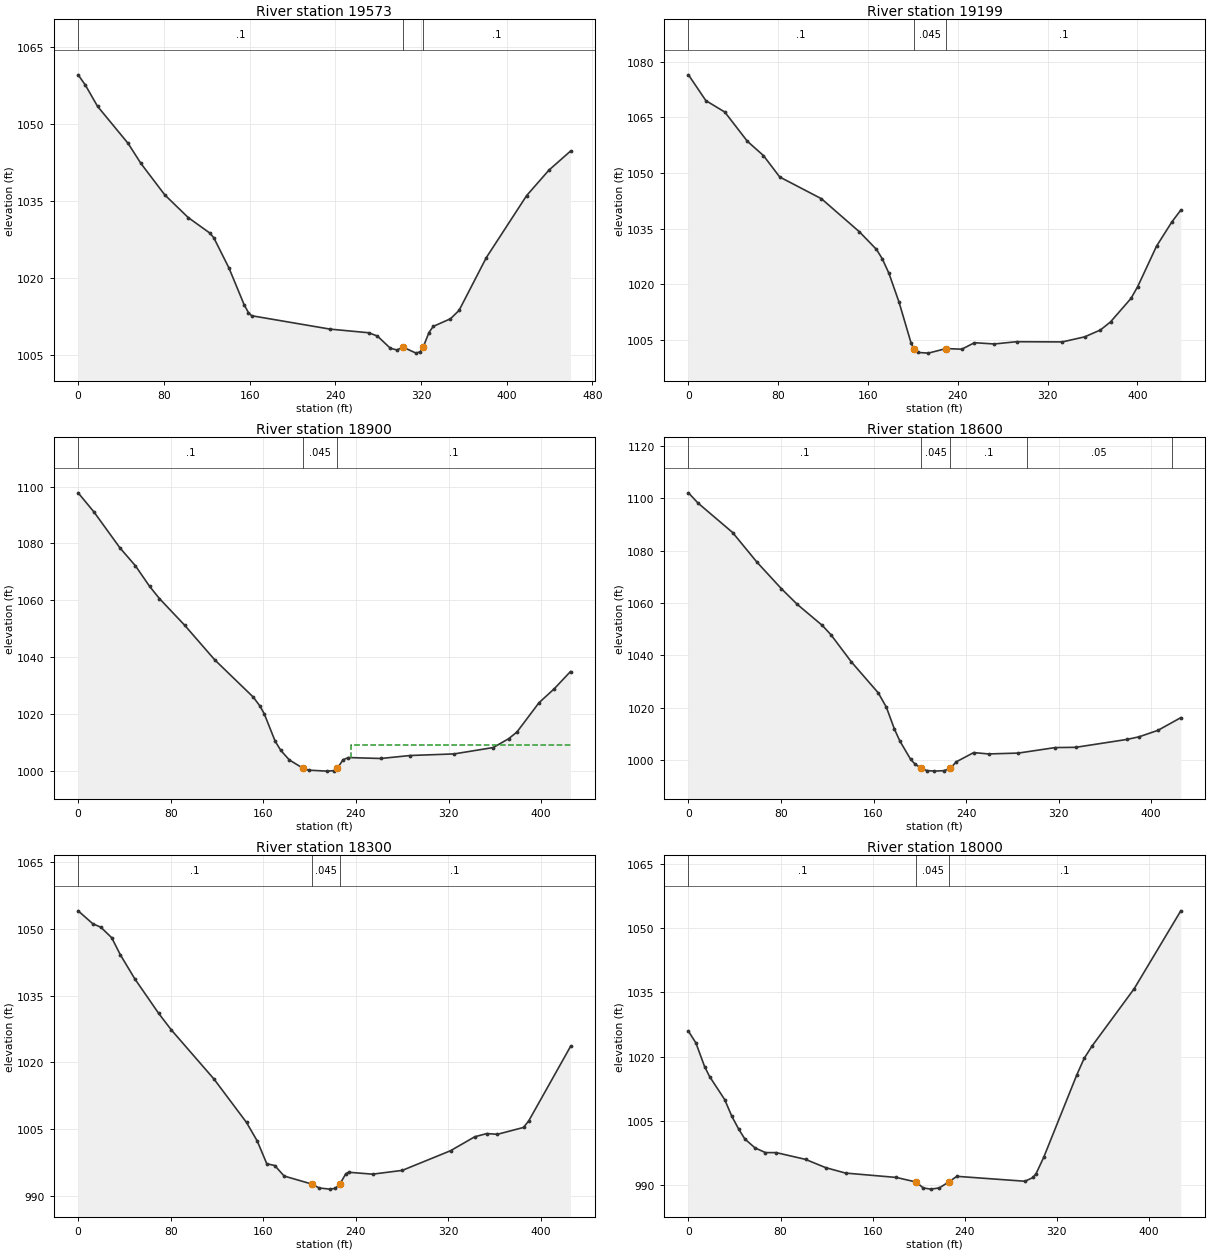
Type RM Length L Ch R = 1 ,19573   ,367.7,373.4,373.1
XS GIS Cut Line= 2
1676006.68677701 545630.978676551675742.21810078546006.736033228
#Sta/Elev= 30
       0 1059.65     6.7 1057.66    18.1 1053.51    46.6 1046.29    58.6 1042.37
    80.8 1036.26   102.7 1031.83   122.8 1028.82   126.6 1027.89   140.8 1021.97
   154.9 1014.84   158.9 1013.31   161.9 1012.69   235.1 1010.08   271.2 1009.37
   279.3 1008.73   291.3 1006.36   297.4 1006.02   303.3 1006.55   315.4  1005.4
   319.4 1005.68   322.1 1006.62   327.4 1009.42   331.4 1010.61   347.5  1012.1
   355.5 1013.73   380.9 1024.01   418.6 1036.12   439.4 1041.08   459.5 1044.78
#Mann= 3 ,-1,0
       0      .1       0   303.3    .045       0   322.1      .1       0
Bank Sta=303.3,322.1
XS Rating Curve= 0 ,0
Exp/Cntr(USF)=0,0
Exp/Cntr=0.3,0.1

Type RM Length L Ch R = 1 ,19199   ,298.3,299.4,295.1
XS GIS Cut Line= 6
1675765.06041117545465.467437416  1675698.390597545522.136287332
1675641.24504201545570.7100090831675562.97387309 545635.71151951
1675500.23384109 545686.425656931675432.86619367545751.598098755
#Sta/Elev= 30
       0 1076.48    15.5 1069.53    32.4 1066.44    52.5 1058.56    66.8 1054.72
    81.3 1048.94   118.5 1043.07   152.3 1034.16   167.5 1029.41   172.7 1026.87
   178.6 1022.96   187.6 1015.19   198.3  1004.2  200.59 1002.69   204.2 1001.64
   213.7 1001.45   229.5 1002.68   243.5 1002.51   254.8 1004.26   272.4 1003.92
   292.4 1004.53     333 1004.47     353 1005.84     367 1007.69     376 1009.87
   394.2 1016.19   400.2 1019.38     417  1030.3   430.7 1036.85   438.6 1040.02
#Mann= 3 ,-1,0
       0      .1       0  200.59    .045       0   229.5      .1       0
Bank Sta=200.59,229.5
XS Rating Curve= 0 ,0
Exp/Cntr(USF)=0,0
Exp/Cntr=0.3,0.1

Type RM Length L Ch R = 1 ,18900   ,297.7,299.9,301.1
XS GIS Cut Line= 6
1675520.96870776545280.4126894181675456.26050384545339.698003918
1675404.28718258545393.7792605911675335.97268668545466.807657838
1675285.50592409545522.2980324181675227.29081742545587.657153666
#Sta/Elev= 30
       0 1097.78    13.9 1090.93    36.2 1078.38    49.5 1072.13    61.7 1064.93
    70.2 1060.63    91.9 1051.31     118 1039.09   151.2 1026.04   156.9 1022.95
   160.7 1020.19   170.2 1010.49     175 1007.31   182.4 1003.93  194.331000.987
     199 1000.34   214.9    1000   220.8 1000.16  223.881000.987   228.8    1004
   233.5 1004.77   261.3 1004.44   286.9 1005.49   324.8 1006.05   358.6 1008.29
   371.8 1011.38     379 1013.72   398.1 1024.04   411.3 1028.95   425.3    1035
#Mann= 3 ,-1,0
       0      .1       0  194.33    .045       0  223.88      .1       0
#XS Ineff= 2 , 0
                          235.38         1009.08
Permanent Ineff=
       F       F
Bank Sta=194.33,223.88
XS Rating Curve= 0 ,0
Exp/Cntr(USF)=0,0
Exp/Cntr=0.3,0.1

Type RM Length L Ch R = 1 ,18600   ,300.6,300.1,298.7
XS GIS Cut Line= 6
1675330.16298701545077.0899333361675262.66180967545132.759769499
1675204.80693851545180.4811307491675127.74278818545244.208037421
1675072.30950008545294.9366105051675010.51041108545357.519818679
#Sta/Elev= 30
       0 1102.09     8.3 1098.17    38.2 1086.93    59.2 1075.63    80.2 1065.55
    94.1 1059.49   115.7 1051.47   123.2  1047.9   140.8 1037.56   164.1  1025.7
   171.1 1020.23     178 1011.95   182.7 1007.38     192 1000.38   195.5  998.71
   201.1996.8827     206  996.07   212.5  995.84     221  996.02  226.25  996.88
   231.6  999.42   246.6 1002.92   259.4  1002.4   285.2 1002.73     317 1004.83
   334.8 1004.93   379.3 1007.96   389.6 1008.96   405.8  1011.4   425.6 1016.25
#Mann= 5 ,-1,0
       0      .1       0   201.1    .045       0  226.25      .1       0
  292.49     .05       0  417.63      .1       0
Bank Sta=201.1,226.25
XS Rating Curve= 0 ,0
Exp/Cntr(USF)=0,0
Exp/Cntr=0.3,0.1

Type RM Length L Ch R = 1 ,18300   ,299.1,300,296.5
XS GIS Cut Line= 6
1675106.58436592544869.9538646791675036.88535833544923.663074836
1674982.55541451544975.366711587  1674910.116583545044.305878177
1674855.77745284545095.9996724281674792.39831451545156.302045256
#Sta/Elev= 30
       0 1054.05    12.6 1051.16    19.6 1050.37      29 1048.01    36.5 1044.16
    48.9  1038.8    69.6 1031.02    80.4 1027.35   117.5 1016.24   145.5 1006.53
   154.8 1002.35     163  997.26   169.9  996.86     178   994.5  201.94992.6959
   208.3  991.82   217.4  991.56   222.2  991.73  226.15 992.695   231.3     995
   233.7  995.35   254.5  994.92   280.1  995.77   321.8 1000.18   342.7 1003.31
   353.2 1004.04   362.3 1003.87   384.9 1005.41   389.5 1006.93   425.5 1023.59
#Mann= 3 ,-1,0
       0      .1       0  201.94    .045       0  226.15      .1       0
Bank Sta=201.94,226.15
XS Rating Curve= 0 ,0
Exp/Cntr(USF)=0,0
Exp/Cntr=0.3,0.1

Type RM Length L Ch R = 1 ,18000   ,259.2,260,255.7
XS GIS Cut Line= 6
1674882.76985292544654.6793608371674824.73059893544720.159872919
  1674774.982995544776.2860729991674708.65209092544851.120569006
1674660.87528358544908.9941409231674616.88127708544987.777776003
#Sta/Elev= 30
       0 1025.95     6.5 1023.19      14  1017.7    18.4 1015.34    31.5 1009.97
    37.6 1006.12    43.6  1003.1      49 1000.77    57.8   998.7    66.9  997.59
    76.2  997.59   101.7  996.01   119.2  994.08   136.5  992.81   180.6  991.79
     198990.7082     204  989.33   210.7  989.06     218  989.35  226.02990.7072
   233.2  992.05   292.4   990.9   299.4  991.78   302.1   992.7   308.7   996.5
   337.5 1015.79   343.8 1019.59   350.7 1022.49   387.3 1035.87   427.8 1054.06
#Mann= 3 ,-1,0
       0      .1       0     198    .045       0  226.02      .1       0
Bank Sta=198,226.02
XS Rating Curve= 0 ,0
Exp/Cntr(USF)=0,0
Exp/Cntr=0.3,0.1