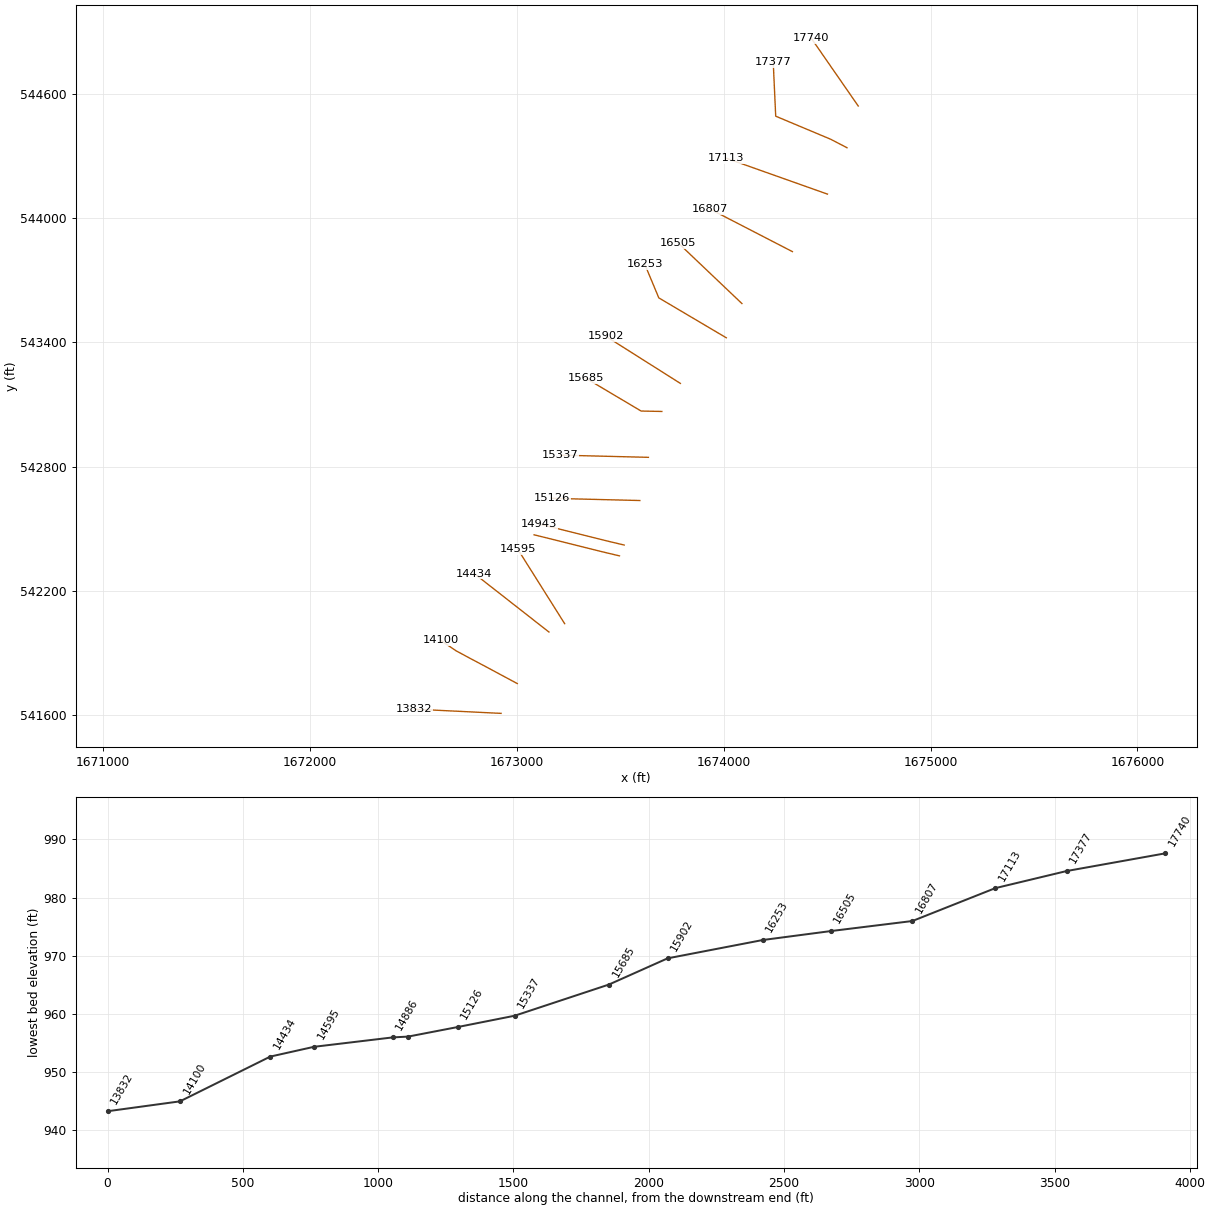
HEC-RAS study TurkeyRn.prj: TurkeyRn

--- TurkeyRn.g01 (geometry) --- (continued)

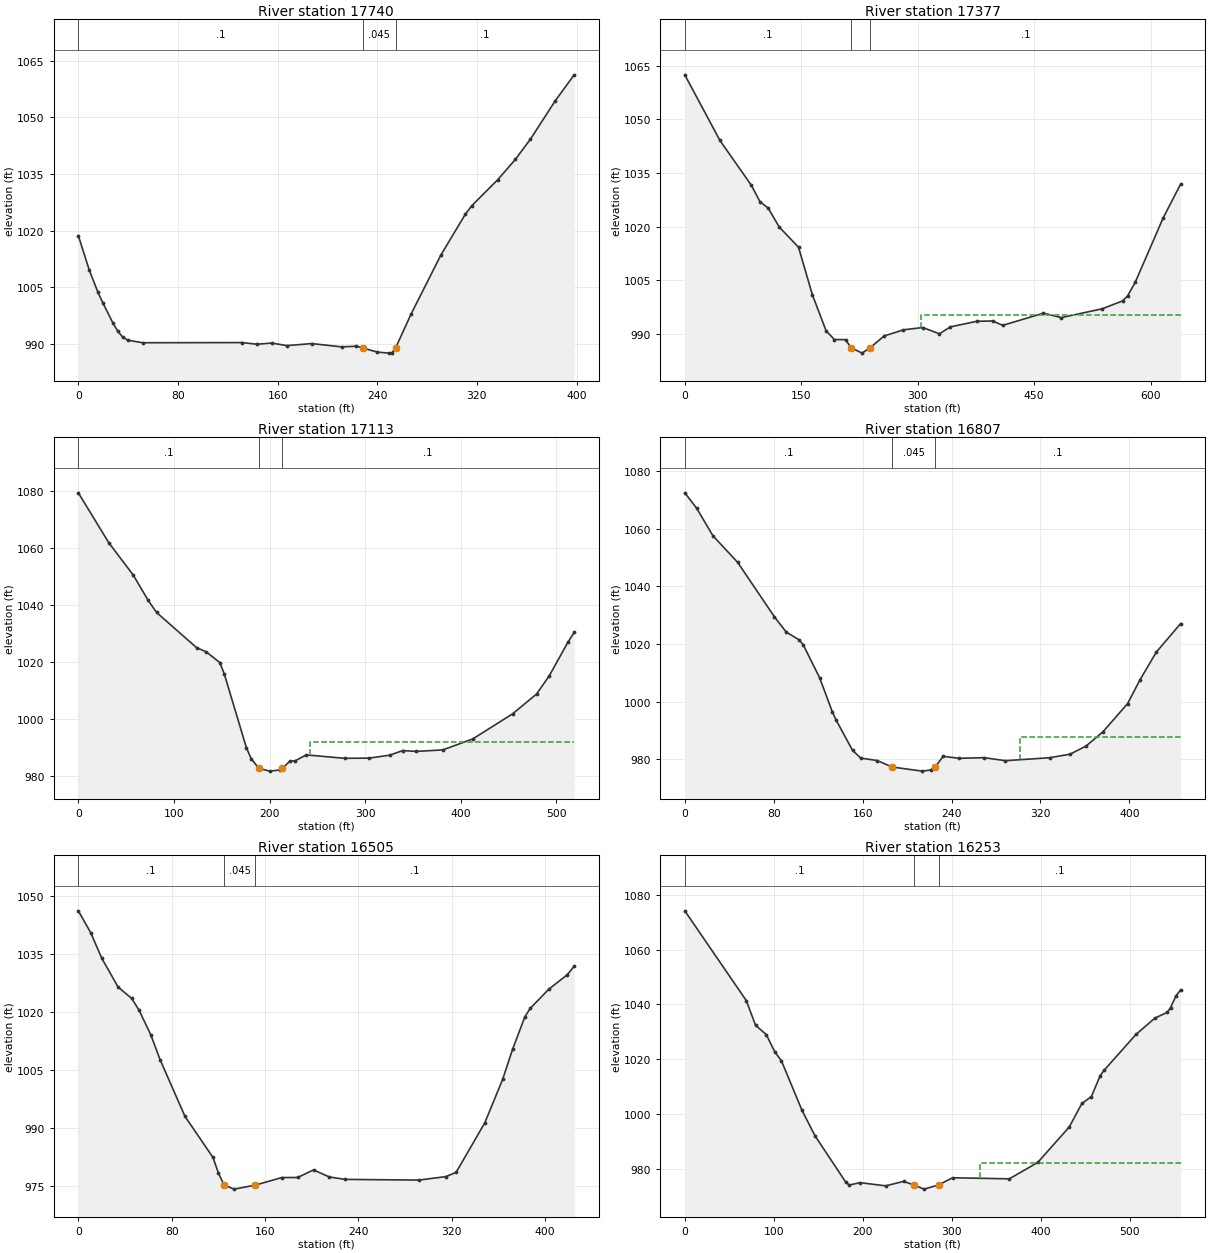
Type RM Length L Ch R = 1 ,17740   ,351.2,363.1,366.8
XS GIS Cut Line= 2
1674650.57868807544543.8852347291674423.94036672544871.201669277
#Sta/Elev= 30
       0 1018.71     8.9 1009.47    15.8 1003.65    19.8 1000.82    27.8  995.56
    31.8  993.34    35.7  991.81    39.7  991.02    51.7  990.34   131.5  990.38
   143.3  989.95   155.5  990.25   167.4  989.58   187.4  990.12   211.3  989.25
   223.3  989.42  228.17988.9833     240  987.87   249.4  987.59   251.8  987.71
  254.77 988.982   267.2  997.96   291.1 1013.57   310.7 1024.35   315.9 1026.62
   336.7 1033.48     351 1038.92     363 1044.24   382.9 1054.38   398.1 1061.27
#Mann= 3 ,-1,0
       0      .1       0  228.17    .045       0  254.77      .1       0
Bank Sta=228.17,254.77
XS Rating Curve= 0 ,0
Exp/Cntr(USF)=0,0
Exp/Cntr=0.3,0.1

Type RM Length L Ch R = 1 ,17377   ,263.4,264.3,264.8
XS GIS Cut Line= 4
1674596.15599024544342.1447873331674517.76867982544382.918984003
1674251.75715712544494.6740201241674239.76931805544756.301307401
#Sta/Elev= 30
       0 1062.47    45.2 1044.12    85.9  1031.5    96.8 1026.96   107.4 1025.17
   121.6 1019.88   146.5 1014.21   164.4 1000.89   182.1  990.78   192.8  988.37
   207.1  988.33  214.12986.1084   228.4  984.56  238.95986.1078   256.8  989.36
   281.7  991.08   306.6  991.73     328  989.97   342.2  991.91   376.5  993.48
   396.5  993.56   409.6  992.34   462.1  995.74   485.1   994.5   537.7  996.97
     564  999.17   570.5 1000.59   580.4 1004.43   616.2 1022.37   638.8 1031.88
#Mann= 3 ,-1,0
       0      .1       0  214.12    .045       0  238.95      .1       0
#XS Ineff= 2 , 0
                          303.75          995.36
Permanent Ineff=
       F       F
Bank Sta=214.12,238.95
XS Rating Curve= 0 ,0
Exp/Cntr(USF)=0,0
Exp/Cntr=0.3,0.1

Type RM Length L Ch R = 1 ,17113   ,304.1,306,303.7
XS GIS Cut Line= 2
1674501.89148023544117.6559643631674013.15508851544291.170176382
#Sta/Elev= 30
       0  1079.3    31.8 1061.81    57.4 1050.45    72.9 1041.63    81.8 1037.31
   123.6 1024.98     134 1023.43     148  1019.7   152.6 1015.79   175.8  989.83
   180.8  985.94  188.97982.5646   200.2  981.61   210.6  982.01  213.37 982.564
   221.1  985.05   227.1  985.29   238.5  987.31   278.4  986.11   304.1  986.17
   325.5   987.2   339.4  988.83   353.4  988.53   381.2  989.06   412.6  992.92
   454.3 1001.74   479.3 1008.68   492.6 1015.09   512.2 1026.94   518.6  1030.3
#Mann= 3 ,-1,0
       0      .1       0  188.97    .045       0  213.37      .1       0
#XS Ineff= 2 , 0
                          242.17          991.87
Permanent Ineff=
       F       F
Bank Sta=188.97,213.37
XS Rating Curve= 0 ,0
Exp/Cntr(USF)=0,0
Exp/Cntr=0.3,0.1

Type RM Length L Ch R = 1 ,16807   ,305.7,301.5,297.4
XS GIS Cut Line= 2
1674332.47928683543839.5143245011673936.23818784544044.356461611
#Sta/Elev= 30
       0 1072.38    10.6 1067.09    25.3 1057.51    47.5 1048.32    80.7  1029.4
    91.3 1024.11   102.9 1021.44   106.6 1019.71   121.4 1008.22   132.7  996.54
   136.1  993.68   150.9  983.18   158.3  980.48   173.1  979.63  186.63977.3784
   213.7  975.96   221.1  976.35  225.18977.3775   232.5  981.09   246.9   980.4
   269.2  980.62   288.5  979.58   328.2   980.6   346.7  981.84     361  984.65
   376.2  989.58   398.4  999.36   409.4 1007.49   424.2 1017.18   446.1 1027.08
#Mann= 3 ,-1,0
       0      .1       0  186.63    .045       0  225.18      .1       0
#XS Ineff= 2 , 0
                          301.81          987.82
Permanent Ineff=
       F       F
Bank Sta=186.63,225.18
XS Rating Curve= 0 ,0
Exp/Cntr(USF)=0,0
Exp/Cntr=0.3,0.1

Type RM Length L Ch R = 1 ,16505   ,248.3,251.7,254.6
XS GIS Cut Line= 6
1674088.50353883543588.3243398211674025.12472858543648.651646985
1673970.80036216543700.3608611511673898.36776424543769.306917487
1673844.04372591543821.0164597321673780.66524375543881.344094991
#Sta/Elev= 30
       0 1046.26    10.6 1040.61    20.1 1033.98    34.1 1026.53    45.8 1023.57
    52.1 1020.51      62 1014.24    70.2 1007.65    91.4  993.07   115.4  982.44
     120  978.46  124.96  975.27   133.6  974.23   151.7  975.27   174.4  977.22
     188  977.24   201.6  979.21   215.1  977.38   228.7  976.75   292.1  976.57
   315.1  977.48   323.8  978.56   348.4  991.39   363.7 1002.63   372.2  1010.4
   382.7  1018.8   387.3    1021   403.1 1025.93     419  1029.7     425 1031.91
#Mann= 3 ,-1,0
       0      .1       0  124.96    .045       0   151.7      .1       0
Bank Sta=124.96,151.7
XS Rating Curve= 0 ,0
Exp/Cntr(USF)=0,0
Exp/Cntr=0.3,0.1

Type RM Length L Ch R = 1 ,16253   ,346.9,351.4,343.9
XS GIS Cut Line= 3
1674012.99468958543422.6713261751673686.88961954543615.757121588
1673618.33946884543779.983109094
#Sta/Elev= 30
       0 1074.14      69 1041.45    79.5 1032.42    91.5 1029.04     101 1022.79
   108.6 1019.42   131.5 1001.52   146.2  992.14     181  975.13   184.9  974.19
   196.8  975.05   225.6  973.89   245.9  975.52  257.17974.1977   268.7  972.69
  285.13974.2405   300.8  976.83   364.5  976.44   396.4  982.41   431.8  995.34
     446 1003.91   456.7 1006.44   466.6 1014.07   470.9 1015.99   506.7 1029.06
   527.8 1034.99   541.9 1037.14   545.6 1038.87   551.9 1043.27   556.9 1045.32
#Mann= 3 ,-1,0
       0      .1       0  257.17    .045       0  285.13      .1       0
#XS Ineff= 2 , 0
                          331.84          982.12
Permanent Ineff=
       F       F
Bank Sta=257.17,285.13
XS Rating Curve= 0 ,0
Exp/Cntr(USF)=0,0
Exp/Cntr=0.3,0.1

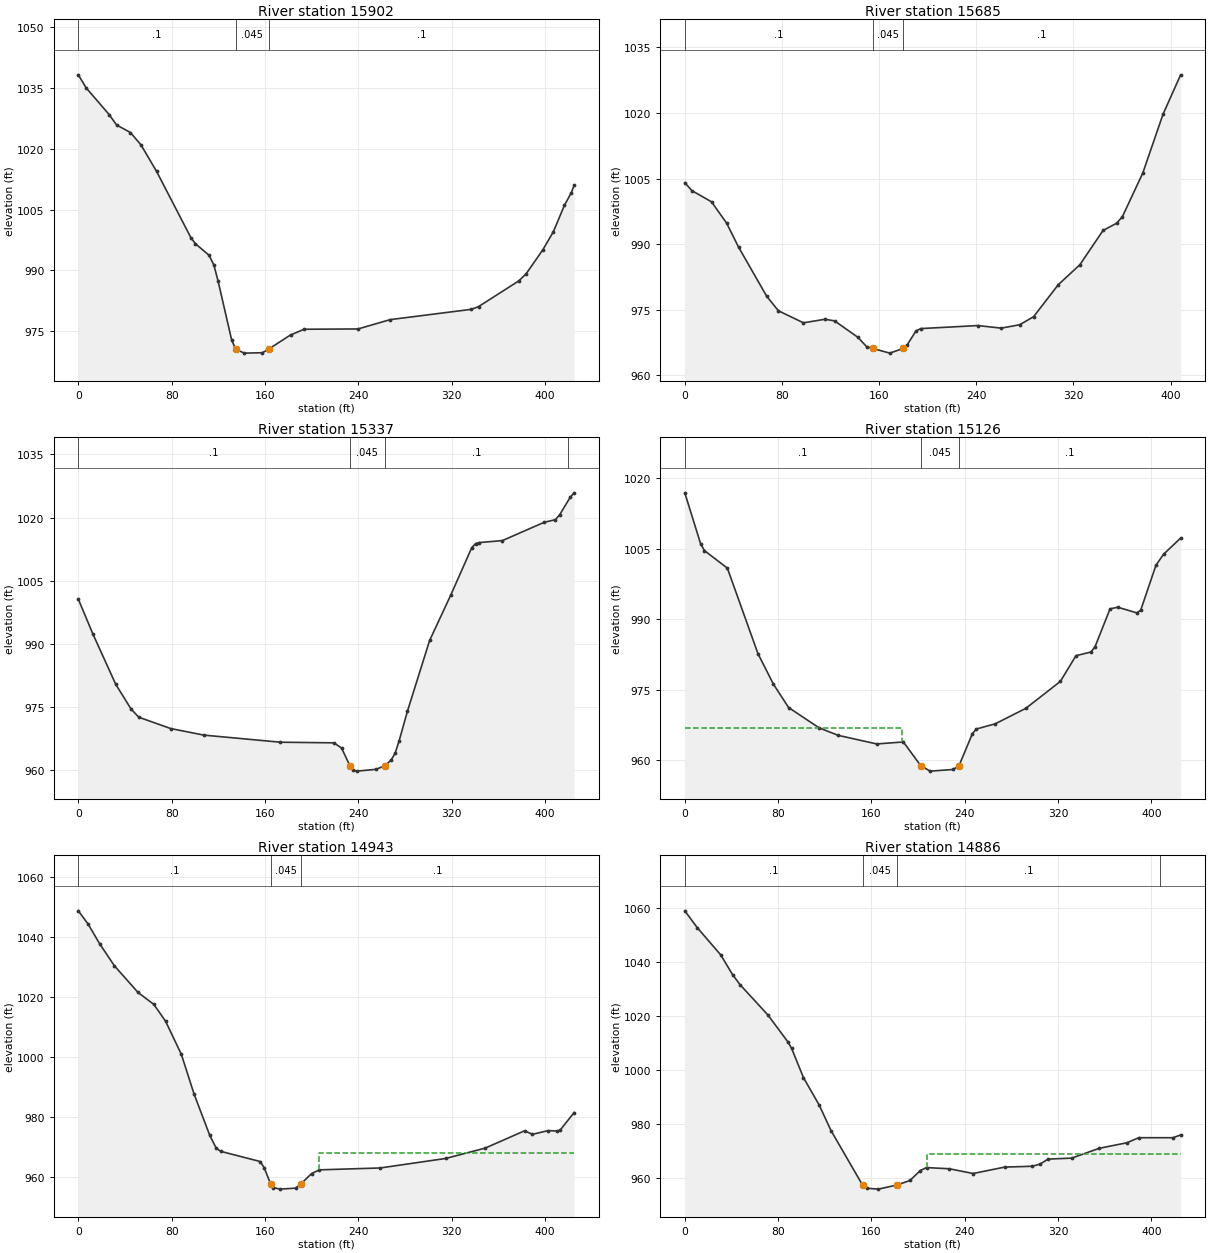
Type RM Length L Ch R = 1 ,15902   ,216.6,217,217.1
XS GIS Cut Line= 6
1673791.09014803543202.0681199551673717.16870794543248.885283527
1673653.80728611543289.014468369 1673569.3254997  543342.5196107
1673505.96407786543382.6487955271673432.04263778543429.465959114
#Sta/Elev= 30
       0 1038.28     6.6  1035.1    26.6  1028.4    32.8 1025.89    44.7 1024.03
    53.8 1020.93    67.1 1014.41    96.5  998.05   100.4  996.55     112  993.73
   116.2  991.29   119.8  987.34   131.4  972.81  134.78 970.552   142.2  969.54
   157.8  969.64  163.25970.5546   181.9  974.03   193.6  975.44   239.7  975.51
   267.4  977.82   336.9  980.36   343.1  981.04   377.6  987.39   383.9  989.16
   398.3  995.13   407.2  999.54   416.6 1006.01   422.6  1009.2     425    1011
#Mann= 3 ,-1,0
       0      .1       0  134.78    .045       0  163.25      .1       0
Bank Sta=134.78,163.25
XS Rating Curve= 0 ,0
Exp/Cntr(USF)=0,0
Exp/Cntr=0.3,0.1

Type RM Length L Ch R = 1 ,15685   ,341.5,348.1,353.5
XS GIS Cut Line= 3
1673701.40691726543066.3339490611673601.39005537543068.337834089
1673336.45437601543225.917499765
#Sta/Elev= 30
       0 1004.04     5.9 1002.21      22  999.67    34.5  994.76    44.3  989.28
    67.3  978.11    77.1  974.72    97.7  971.97   115.4  972.78   123.3  972.42
   142.5  968.66   149.8  966.49  154.84 966.096   168.8  965.03  179.78966.0961
   183.2  966.96   190.4  970.11   194.4  970.65   241.4  971.34   260.5  970.75
   275.7  971.52   287.2  973.36   307.6  980.71   325.3  985.25   344.4   993.1
   355.5  994.74   360.3  996.24   377.1 1006.22   393.8  1019.7   408.3 1028.73
#Mann= 3 ,-1,0
       0      .1       0  154.84    .045       0  179.78      .1       0
Bank Sta=154.84,179.78
XS Rating Curve= 0 ,0
Exp/Cntr(USF)=0,0
Exp/Cntr=0.3,0.1

Type RM Length L Ch R = 1 ,15337   ,210.5,211,210.7
XS GIS Cut Line= 2
1673636.68995771542844.4487372991673211.76101755542855.026472053
#Sta/Elev= 30
       0 1000.58    12.4  992.35    32.1  980.31    45.2  974.45    51.8   972.5
    79.2   969.8   107.6  968.24   173.2  966.55   219.2   966.4   225.7  965.15
  232.81960.9645   235.6  959.88   238.9  959.67   255.3   960.1  262.92960.9652
   268.4  962.39   271.7     964     275  966.84   282.1  973.87   301.2  990.77
   319.2 1001.49   337.3 1012.83   340.6  1013.8   343.9 1014.05   363.6 1014.52
   399.4 1018.87     409 1019.49   412.8 1020.71   421.8 1024.86   425.1 1025.88
#Mann= 4 ,-1,0
       0      .1       0  232.81    .045       0  262.92      .1       0
     420     .06       0
Bank Sta=232.81,262.92
XS Rating Curve= 0 ,0
Exp/Cntr(USF)=0,0
Exp/Cntr=0.3,0.1

Type RM Length L Ch R = 1 ,15126   ,185.2,182.9,178.4
XS GIS Cut Line= 2
1673595.10888724542635.5511458451673170.17994708542646.128880599
#Sta/Elev= 30
       0 1016.88    13.5  1006.1    16.8 1004.61    36.5 1000.87    62.7  982.71
      76   976.2      89  971.24   115.2  966.91   131.6  965.32   164.5   963.5
   187.4  963.92  202.42 958.837   210.4  957.72   230.1  958.07  235.02 958.836
   246.5  965.63   249.8  966.66   266.2  967.78   292.4  971.07     322   976.8
   335.4  982.26   348.2  983.04   351.7  984.15   364.6  992.22   371.2  992.56
   387.6  991.36   390.9  991.95     404 1001.52   410.6 1003.85   425.1 1007.26
#Mann= 3 ,-1,0
       0      .1       0  202.42    .045       0  235.02      .1       0
#XS Ineff= 2 , 0
          186.64  966.91
Permanent Ineff=
       F       F
Bank Sta=202.42,235.02
XS Rating Curve= 0 ,0
Exp/Cntr(USF)=0,0
Exp/Cntr=0.3,0.1

Type RM Length L Ch R = 1 ,14943   ,56.5,56.9,56.7
XS GIS Cut Line= 6
1673519.86181866 542420.124082531673434.74453482542440.426535362
1673361.98385358542458.6164596021673264.96993999542482.871988529
1673192.20860258542501.0599442811673107.27078033542522.080243448
#Sta/Elev= 30
       0 1048.63     8.4 1044.21    18.2 1037.71    30.9 1030.36    51.2 1021.48
    64.7 1017.52    74.8 1011.91    88.3 1000.91    99.2   987.7   112.7  973.92
   118.2  969.69   122.1  968.64   155.9  965.26   159.3  963.19  164.91957.7344
   166.9  956.62   172.8  956.08   186.4  956.41  190.57957.7354   199.9  961.25
   206.6  962.49   258.8  963.12   314.9  966.28   348.7  969.72   382.5  975.48
   389.2   974.3   402.7  975.54   410.4   975.4   412.9  975.67     425  981.56
#Mann= 3 ,0,0
       0      .1       0  164.91    .045       0  190.57      .1       0
#XS Ineff= 2 , 0
                           206.5          967.99
Permanent Ineff=
       F       F
Bank Sta=164.91,190.57
XS Rating Curve= 0 ,0
Exp/Cntr(USF)=0,0
Exp/Cntr=0.3,0.1

Type RM Length L Ch R = 1 ,14886   ,300.7,291,278
XS GIS Cut Line= 6
1673496.77806845542367.7851427031673411.66078462542388.087595535
1673338.90010337542406.2775197751673241.88618979542430.533048702
1673169.12485237542448.7210044541673084.18703012542469.741303621
#Sta/Elev= 30
       0 1058.88    10.6 1052.69    30.8 1042.58    40.9 1035.32    47.3 1031.59
    71.3 1020.33    88.2  1010.5    91.5 1008.06   101.7   997.2   115.2  987.04
   125.4  977.54  152.33957.4583   155.8  956.28   165.9  955.94  181.78957.4577
     193  959.14   201.8   962.8   207.2  963.91   226.8  963.47   247.1  961.72
   274.2  964.09   297.8   964.4   304.6  965.22   311.4  967.05   331.7  967.41
   355.3  971.05     379  973.09   389.1  974.96   418.4  974.96     425  975.97
#Mann= 4 ,-1,0
       0      .1       0  152.33    .045       0  181.78      .1       0
  407.51     .05       0
#XS Ineff= 2 , 0
                          207.22          968.83
Permanent Ineff=
       F       F
Bank Sta=152.33,181.78
XS Rating Curve= 0 ,0
Exp/Cntr(USF)=0,0
Exp/Cntr=0.3,0.1

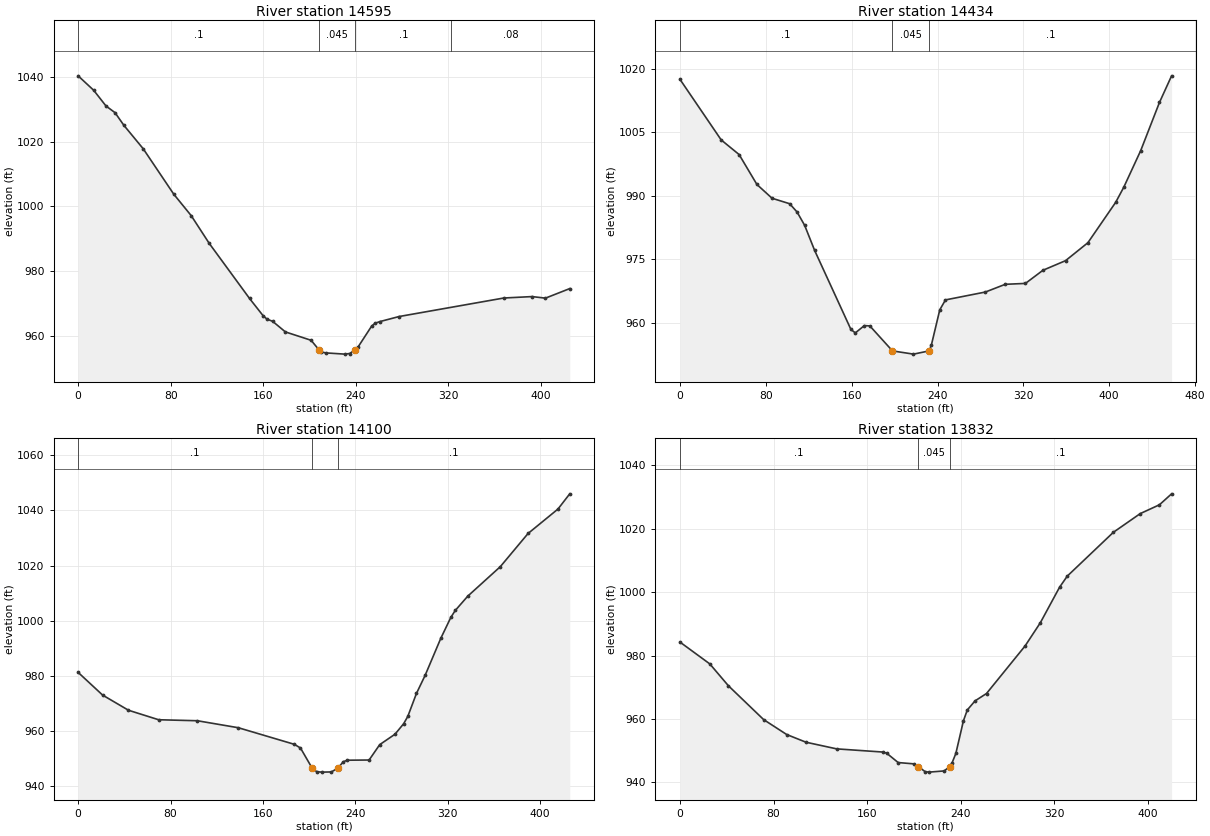
Type RM Length L Ch R = 1 ,14595   ,154.1,161.4,165.7
XS GIS Cut Line= 6
1673231.99300108542039.7673353851673185.39401292542113.826570466
1673145.45183558542177.3061023051673092.19603658542261.945368722
1673052.25353116542325.424572467  1673005.654543542399.483807548
#Sta/Elev= 30
       0 1040.31    13.5 1035.83    24.1 1030.99    31.9 1028.93    39.6    1025
    56.3 1017.76    82.7 1003.73    97.8  997.09   113.3  988.56   148.2  971.51
   159.8  966.24   163.3  965.11   168.1  964.47   179.2  961.18   201.4   958.6
  208.11955.6958   210.2  954.99   214.1   954.7   230.6  954.32   234.7  954.51
  239.75955.6938   241.9  956.47   253.7  962.96   256.7  963.86   260.9  964.38
   277.5  965.94     368  971.66   392.4   972.1     404  971.62     425  974.57
#Mann= 4 ,-1,0
       0      .1       0  208.11    .045       0  239.75      .1       0
   322.5     .08       0
Bank Sta=208.11,239.75
XS Rating Curve= 0 ,0
Exp/Cntr(USF)=0,0
Exp/Cntr=0.3,0.1

Type RM Length L Ch R = 1 ,14434   ,329.9,333.8,335.3
XS GIS Cut Line= 2
1673155.82809684 541999.50291267 1672795.1791927542281.979707771
#Sta/Elev= 30
       0 1017.46    38.4 1003.17    55.1  999.72    71.7  992.66    85.8  989.41
   102.2  988.12   109.1  986.17   116.2  983.01   125.5  977.09   159.3  958.46
   163.4  957.65   171.8  959.37   176.9   959.3  198.01953.3989   217.6  952.64
  232.09953.3978   234.3  954.83   242.1   963.1   247.4  965.43   284.6  967.29
   303.1  969.11   321.9  969.32   338.2  972.42   359.3  974.69   380.1  978.92
     406  988.45   413.5  991.99   429.3 1000.64   446.8 1012.02   458.1 1018.29
#Mann= 3 ,-1,0
       0      .1       0  198.01    .045       0  232.09      .1       0
Bank Sta=198.01,232.09
XS Rating Curve= 0 ,0
Exp/Cntr(USF)=0,0
Exp/Cntr=0.3,0.1

Type RM Length L Ch R = 1 ,14100   ,261.7,267.7,273.1
XS GIS Cut Line= 6
1673003.22013435541749.9811020051672926.17862175541791.391124174
1672860.13938376541826.8881004151672771.82295933541873.796799257
1672705.81193651541909.4801268431672633.01713459541959.101746753
#Sta/Elev= 30
       0  981.18    21.2  972.93    43.6  967.42    69.7  963.97   103.2  963.61
   138.7  961.07   187.2  955.04   192.5   953.7  202.65946.3467   206.6  945.09
   211.1  944.94   219.2  945.01  224.76946.3506   229.6  948.73   233.1  949.27
   251.9  949.34   261.1  954.93   274.3  958.71   281.8  962.52   285.4  965.18
   292.9  973.54   300.4   980.1     314  993.59   322.7 1001.19   326.5 1003.68
   337.4 1008.91   365.5 1019.59   389.5 1031.64   415.4 1040.52   425.6 1046.05
#Mann= 3 ,-1,0
       0      .1       0  202.65    .045       0  224.76      .1       0
Bank Sta=202.65,224.76
XS Rating Curve= 0 ,0
Exp/Cntr(USF)=0,0
Exp/Cntr=0.3,0.1

Type RM Length L Ch R = 1 ,13832   ,341.4,337.4,323.2
XS GIS Cut Line= 2
1672924.72554067 541605.941691921672505.02281168541626.418329168
#Sta/Elev= 30
       0  984.28    25.5  977.39    41.4  970.49    71.5  959.82    91.2  955.11
   107.7  952.68   133.9  950.58   173.3  949.58   176.6  949.23   186.5  946.26
   199.6  945.86  203.73944.9883   209.5   943.4   212.8  943.24   225.9  943.62
  230.42944.9907   232.5   946.1   235.8  949.14   242.3  959.47   245.6  962.86
   252.2  965.72     262  968.05   294.9  983.02     308  990.37   324.4 1001.56
     331 1005.08   370.4 1018.91   393.4 1024.82   409.8  1027.6   420.2 1031.06
#Mann= 3 ,-1,0
       0      .1       0  203.73    .045       0  230.42      .1       0
Bank Sta=203.73,230.42
XS Rating Curve= 0 ,0
Exp/Cntr(USF)=0,0
Exp/Cntr=0.3,0.1