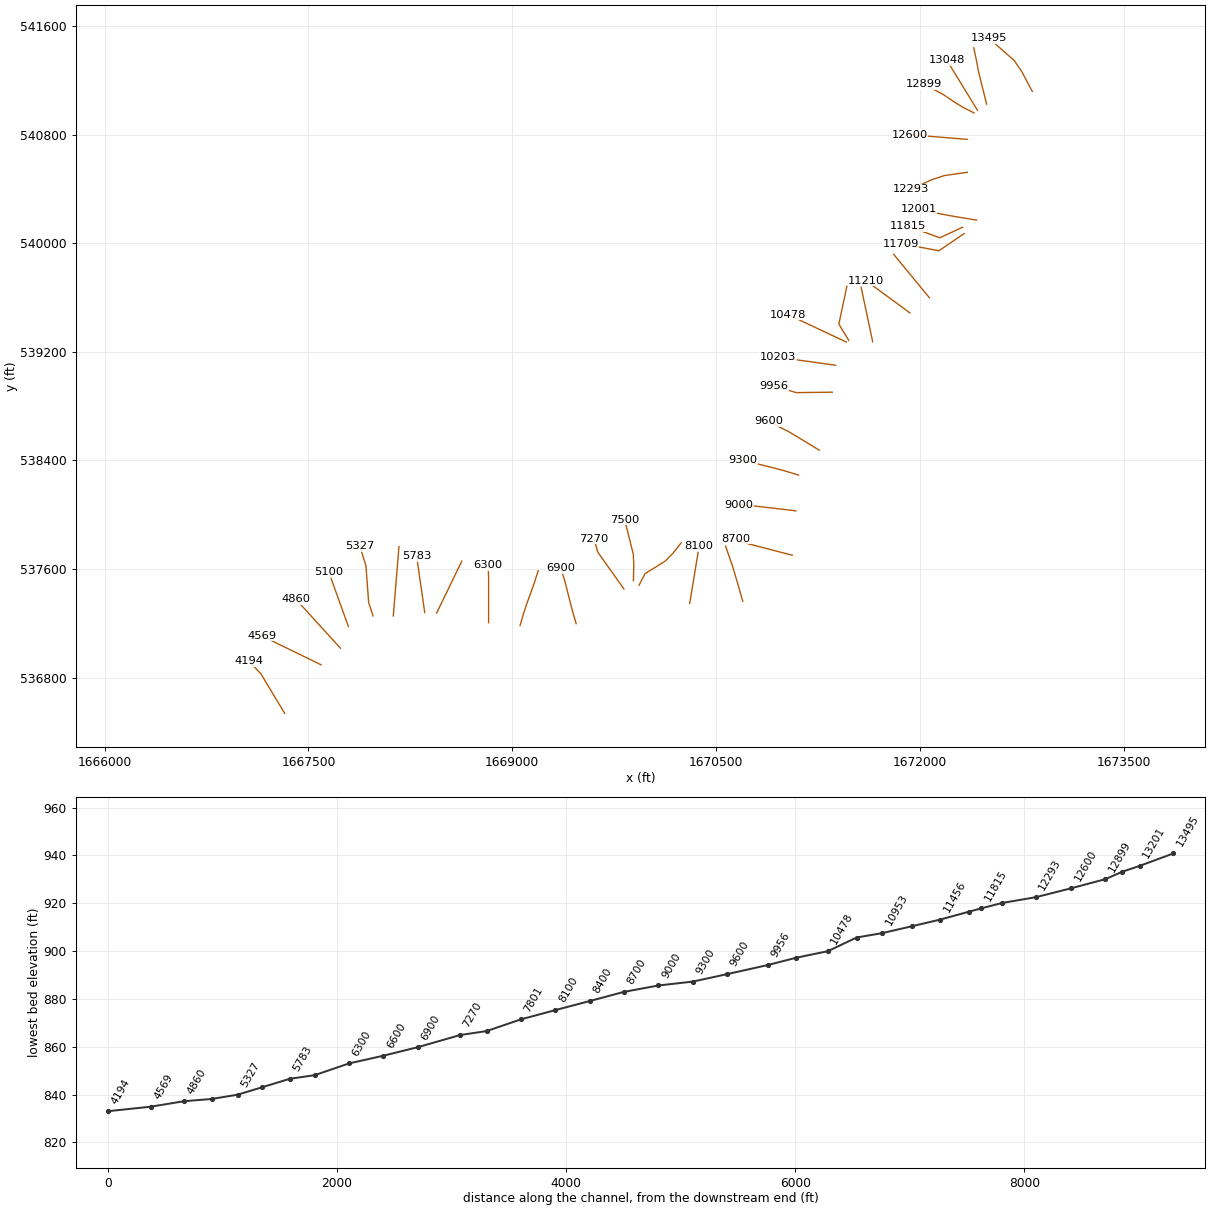
HEC-RAS study TurkeyRn.prj: TurkeyRn

--- TurkeyRn.g01 (geometry) --- (continued)

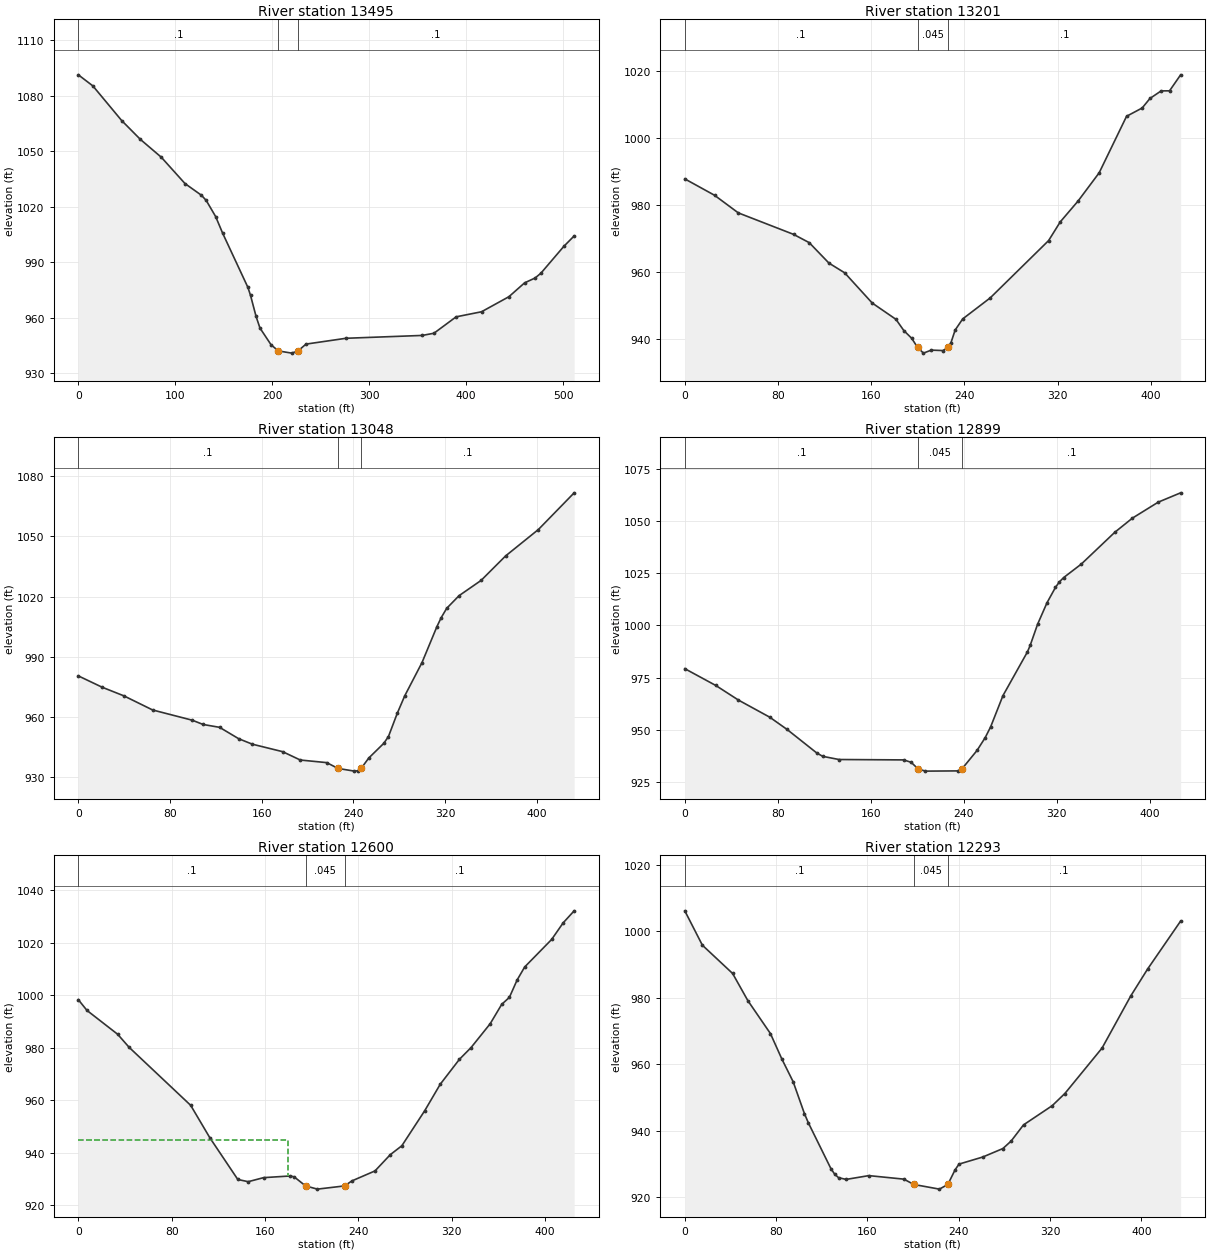
Type RM Length L Ch R = 1 ,13495   ,296.2,294.1,289
XS GIS Cut Line= 5
1672827.97803076541118.4685855061672787.03815201541195.800123751
1672751.94668676541262.0844400081672695.61379418541345.456648588
1672509.30149248541509.351254677
#Sta/Elev= 30
       0 1091.33      15 1085.33    44.7  1066.6    63.9 1056.45    85.5 1046.79
     110 1032.52     127 1026.18   131.9 1023.37   141.6 1014.68   148.8  1005.7
   174.9  976.33   177.6  971.99   183.3  960.64   187.3  954.39   198.8   945.3
  206.29942.0025   220.1  940.82  226.51942.0026   234.8   945.7     276  948.85
   354.6  950.39   366.7  951.57   389.6  960.45   415.8  963.19     444  971.33
   460.2  978.83     471  981.44     477  984.04   500.8  998.65   511.3  1004.2
#Mann= 3 ,-1,0
       0      .1       0  206.29    .045       0  226.51      .1       0
Bank Sta=206.29,226.51
XS Rating Curve= 0 ,0
Exp/Cntr(USF)=0,0
Exp/Cntr=0.3,0.1

Type RM Length L Ch R = 1 ,13201   ,147.3,152.4,154.3
XS GIS Cut Line= 6
1672491.93900467541024.8175260871672470.71660617541109.704823509
1672452.52635384541182.4655047511672429.27640034541279.730730176
1672415.52216275541353.6003330951672397.54188375541439.618861839
#Sta/Elev= 30
       0   987.8    25.5   982.9    45.9  977.62    93.3  971.19   106.8   968.7
   123.7  962.58   137.2  959.67   160.8  950.63   181.2  945.74     188  942.36
   194.7  940.07  199.71937.3517   204.8  935.62   211.5  936.52   221.6  936.39
  225.88 937.352   228.4  938.73     232  942.53   238.5  945.87   262.1  952.16
   312.2  969.32   322.2  974.92   337.5  981.17   355.6  989.62   379.1 1006.54
   392.5 1009.03   399.2 1011.89   408.8 1014.15     416 1014.17   425.5 1018.96
#Mann= 3 ,-1,0
       0      .1       0  199.71    .045       0  225.88      .1       0
Bank Sta=199.71,225.88
XS Rating Curve= 0 ,0
Exp/Cntr(USF)=0,0
Exp/Cntr=0.3,0.1

Type RM Length L Ch R = 1 ,13048   ,141.7,148.7,151.5
XS GIS Cut Line= 2
1672424.51181353540979.7136032331672198.73374363541348.607826723
#Sta/Elev= 30
       0  980.58    20.8  974.93    39.7  970.65    64.8  963.61    99.4  958.51
   108.9  956.38   123.2  954.97   139.9  949.29   151.8  946.57   178.2  942.85
   193.6  938.69   216.7  937.39  226.47934.5037   240.8  933.16   243.6  933.34
  246.68934.5052   253.3  939.66   266.4  946.98   270.5  950.36   278.2  961.96
   284.7  970.63   299.8  987.24   312.8 1005.13   316.5 1009.56   321.3 1014.21
   332.1 1020.52   351.3 1028.11   372.7 1040.31   401.3 1053.46   432.5 1071.73
#Mann= 3 ,-1,0
       0      .1       0  226.47    .045       0  246.68      .1       0
Bank Sta=226.47,246.68
XS Rating Curve= 0 ,0
Exp/Cntr(USF)=0,0
Exp/Cntr=0.3,0.1

Type RM Length L Ch R = 1 ,12899   ,290.8,299.4,309.2
XS GIS Cut Line= 6
1672399.09371792540959.8524329221672320.65128951 540999.75556834
1672256.43980376541038.7981411671672173.70965426541094.988317505
1672107.25670317541130.7963167581672029.11283059541171.266052082
#Sta/Elev= 30
       0  979.26    26.7  971.18    46.2  964.16    73.1  955.95      88  950.07
   113.5  938.79   118.7  937.14   132.7  935.62   188.4  935.43   194.8  934.28
  200.86931.0645   207.1  930.04   234.9  930.15  238.46 931.067   251.5  939.98
   258.5  946.12   263.2   951.3   273.8  966.31   294.8  987.25   297.2   990.4
   303.6 1000.59   311.7 1010.91     319 1018.31   322.3  1020.9     326    1023
   341.2 1029.49     370 1044.75   385.2 1051.57   407.4 1059.24   426.7 1063.73
#Mann= 3 ,-1,0
       0      .1       0  200.86    .045       0  238.46      .1       0
Bank Sta=200.86,238.46
XS Rating Curve= 0 ,0
Exp/Cntr(USF)=0,0
Exp/Cntr=0.3,0.1

Type RM Length L Ch R = 1 ,12600   ,295.9,306.9,309.3
XS GIS Cut Line= 6
1672348.83036701540765.2422578331672261.62286426540772.389881343
1672186.87366992540778.5168375821672087.20785876540786.685456425
1672012.45833634540792.8124126791671925.25083359540799.960036173
#Sta/Elev= 30
       0   998.3     7.4  994.21    33.7  985.14    43.6  980.14    96.3   958.1
   112.7  945.78   136.7  929.89   145.6  929.05   158.8  930.59   181.8  931.23
   185.1  930.86  194.76927.4482   204.9  926.22  228.24927.4472   234.5  929.35
   254.3  933.15   267.4  939.33   277.3  942.72     297  956.12   310.2  966.12
   326.7  975.63   336.6  980.06     353  989.13   362.9  996.51   369.5  999.19
   376.1 1005.78   382.6 1010.74   405.7 1021.21   415.6 1027.54     425  1032.1
#Mann= 3 ,-1,0
       0      .1       0  194.76    .045       0  228.24      .1       0
#XS Ineff= 2 , 0
          179.48  944.82
Permanent Ineff=
       F       F
Bank Sta=194.76,228.24
XS Rating Curve= 0 ,0
Exp/Cntr(USF)=0,0
Exp/Cntr=0.3,0.1

Type RM Length L Ch R = 1 ,12293   ,297.8,292.4,283.3
XS GIS Cut Line= 6
1672350.17813334540522.4592788371672259.66289443540509.840865761
1672181.14861576540498.6187753381672085.09237742540466.917067096
1672017.13844509540435.1805820021671937.86596584540398.159002513
#Sta/Elev= 30
       0 1006.13    15.4   995.8    41.9   987.3    55.2  979.16      75  969.25
      85  961.61    94.9  954.78   104.8  945.18   108.2  942.44     128  928.65
   131.4  926.94   134.7  925.94   141.3  925.42   161.2  926.56   191.9   925.5
  200.59923.9027     223   922.5  230.39923.8999   236.8  928.33   240.2  930.02
     261  932.15   278.6  934.69   285.8  936.93   296.7  941.81   321.8  947.57
   332.9  951.23   365.5   964.9   390.6  980.54   405.3   988.6   434.3 1003.05
#Mann= 3 ,-1,0
       0      .1       0  200.59    .045       0  230.39      .1       0
Bank Sta=200.59,230.39
XS Rating Curve= 0 ,0
Exp/Cntr(USF)=0,0
Exp/Cntr=0.3,0.1

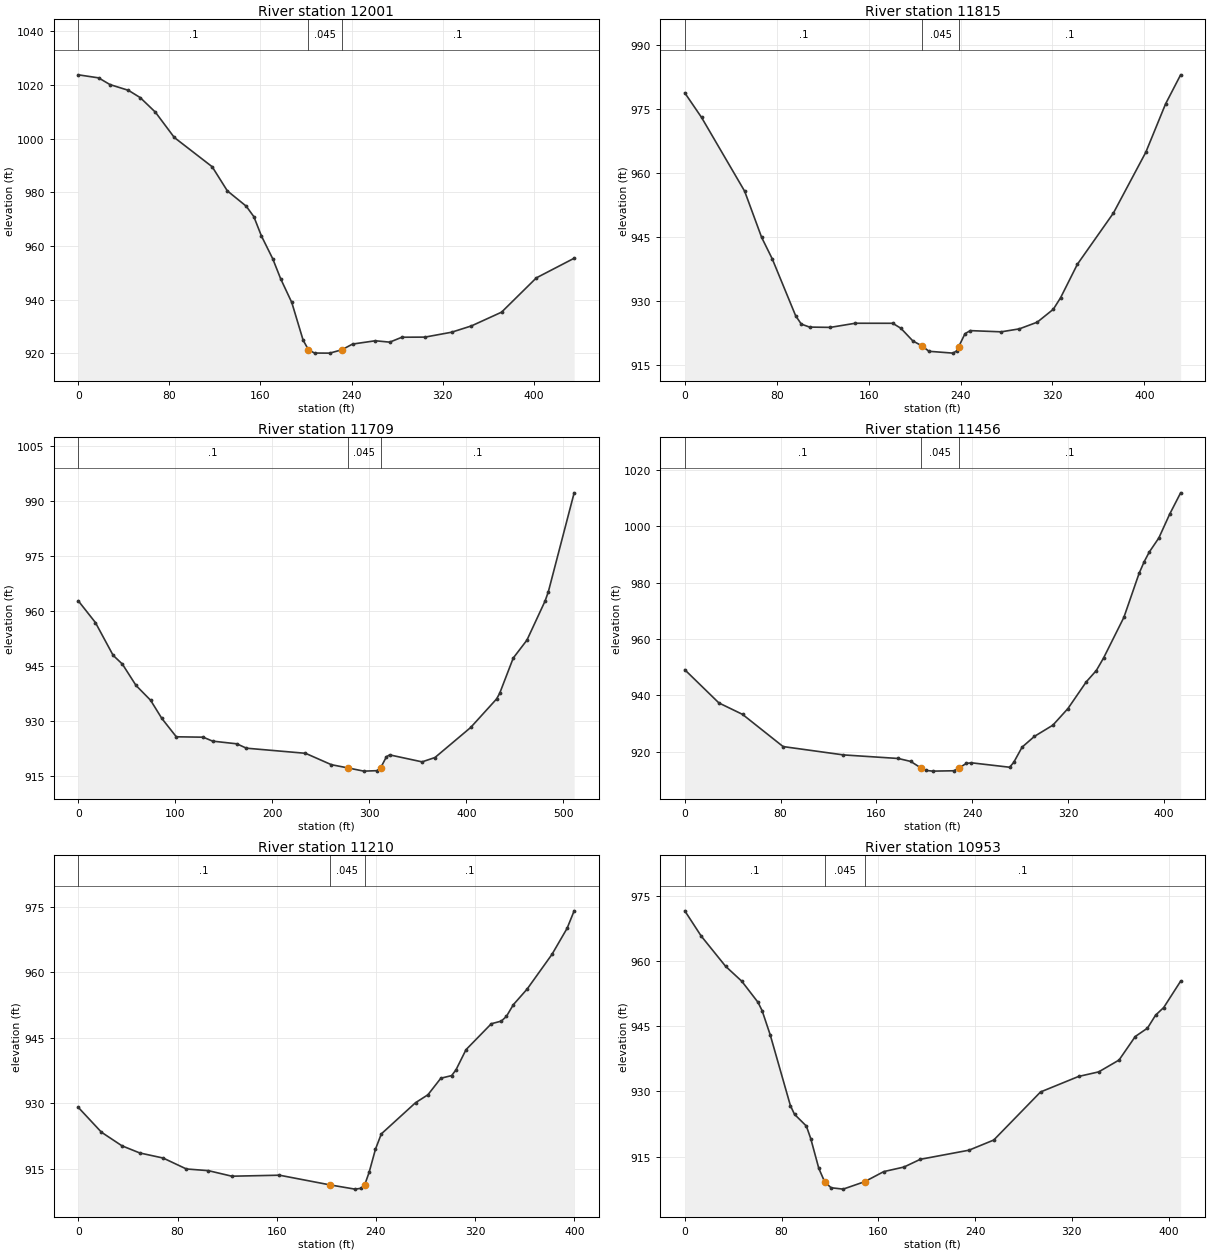
Type RM Length L Ch R = 1 ,12001   ,183.6,185.8,179.2
XS GIS Cut Line= 6
1672418.11631767540170.1909545061672331.80677901 540184.57642442
1672257.82726817540196.9071084261672158.30548559540215.038961917
1672083.52545142 540230.797788681671990.95936359540254.154697344
#Sta/Elev= 30
       0 1023.72    17.8 1022.59    27.8 1020.09      44 1017.95    54.4 1015.23
    67.7 1009.82    84.3  1000.4   117.6   989.5   130.9  980.53   147.5  974.82
   154.2  970.92   160.8  963.79   170.8  955.24   177.8  947.75   187.5     939
   197.5  924.92   202.2921.3669   207.5  920.15   220.9  920.12  231.49921.3666
   240.9  923.49   260.9  924.72   273.6  924.21   284.3  926.04   304.5  926.08
   327.9   927.9   345.4  930.26   371.8  935.36   402.4  948.14   435.6  955.44
#Mann= 3 ,-1,0
       0      .1       0   202.2    .045       0  231.49      .1       0
Bank Sta=202.2,231.49
XS Rating Curve= 0 ,0
Exp/Cntr(USF)=0,0
Exp/Cntr=0.3,0.1

Type RM Length L Ch R = 1 ,11815   ,102.4,106,108.2
XS GIS Cut Line= 3
 1672315.3220331540118.1348743521672147.75749899540040.337054943
1671915.86015267540124.867377955
#Sta/Elev= 30
       0  978.76    14.6     973    52.1  955.73    66.9  944.91    76.1   939.9
    96.5  926.56   101.4  924.61   108.6  923.91   126.7  923.84   148.4  924.81
     181   924.8   188.1  923.63   198.5  920.67   206.8  919.45   212.5  918.24
   233.5  917.81     237   918.4  238.44  919.33   243.9  922.36   248.5  923.08
   275.4   922.8   291.2  923.49   306.8  925.06   320.8  928.09   327.1  930.78
   341.7  938.61   373.1  950.62   401.3  964.86   418.5  976.18   431.6  982.99
#Mann= 3 ,0,0
       0      .1       0   206.8    .045       0  238.44      .1       0
Bank Sta=206.8,238.44
XS Rating Curve= 0 ,0
Exp/Cntr(USF)=0,0
Exp/Cntr=0.3,0.1

Type RM Length L Ch R = 1 ,11709   ,264,253.3,241.3
XS GIS Cut Line= 3
 1672326.4559823540071.3775277311672141.23516072539944.827781887
1671859.28311776539997.750354499
#Sta/Elev= 30
       0  962.75    17.6  956.86    35.9  947.93    45.4  945.56    59.5  939.74
    74.5  935.72    86.1  930.77     101  925.78   128.8  925.67   138.4   924.6
   163.4  923.87   173.3  922.68   234.2  921.29   260.9  918.19  277.91917.3162
   294.3  916.44   307.7  916.56  311.61917.3139   317.7  920.36     321  920.86
   354.4  918.96   367.7  920.14   404.5  928.31   431.2  936.07   434.4   937.6
   448.4   947.2   462.5  952.07   481.2   962.7   484.6  965.25   511.2  992.14
#Mann= 3 ,-1,0
       0      .1       0  277.91    .045       0  311.61      .1       0
Bank Sta=277.91,311.61
XS Rating Curve= 0 ,0
Exp/Cntr(USF)=0,0
Exp/Cntr=0.3,0.1

Type RM Length L Ch R = 1 ,11456   ,238.7,246.1,247
XS GIS Cut Line= 2
1672070.87949262  539598.46860381671807.93317026539918.335612578
#Sta/Elev= 30
       0  949.12    28.5  937.33    48.2  933.28    82.1  921.84   132.5  918.88
   178.3  917.61   188.7  916.56   196.9914.3314   201.1  913.38   207.1  913.12
   224.8  913.25  229.36914.3309     235  915.83   239.3  916.08   271.3   914.5
   274.7  916.22   281.7  921.64     292  925.46   307.4  929.44     320  935.35
   335.3  944.83   343.7  948.85   349.7  953.26   366.7  967.72   379.4  983.33
   383.7  987.53   387.9  990.91   395.9  995.92   404.9 1004.33   414.1 1011.95
#Mann= 3 ,-1,0
       0      .1       0   196.9    .045       0  229.36      .1       0
Bank Sta=196.9,229.36
XS Rating Curve= 0 ,0
Exp/Cntr(USF)=0,0
Exp/Cntr=0.3,0.1

Type RM Length L Ch R = 1 ,11210   ,262.8,256.2,239.9
XS GIS Cut Line= 2
1671927.30655578539486.8640700471671605.29521019539723.745979445
#Sta/Elev= 30
       0  929.06    18.6  923.39    35.2  920.26    49.5  918.63    68.4  917.46
    87.1  914.96   104.9  914.57   123.8   913.3   162.2  913.53  202.72 911.321
     223  910.34   227.9  910.52   230.9  911.32   234.5  914.21   239.6   919.5
   244.3  922.99   271.9  930.14   281.9  931.96   292.3  935.75     301  936.35
   304.5  937.66   312.6  942.29     333  948.23   341.1  948.84   345.2  949.93
   350.8  952.61   361.9  956.18   381.9  964.12   394.1  970.09   399.8   974.1
#Mann= 3 ,-1,0
       0      .1       0  202.72    .045       0   230.9      .1       0
Bank Sta=202.72,230.9
XS Rating Curve= 0 ,0
Exp/Cntr(USF)=0,0
Exp/Cntr=0.3,0.1

Type RM Length L Ch R = 1 ,10953   ,228.2,223.7,214.1
XS GIS Cut Line= 2
1671653.41184804539274.6573595441671568.28241185539675.629341598
#Sta/Elev= 30
       0  971.63    13.5  965.84    33.7  958.86    47.1  955.41    60.5  950.56
    63.9  948.64    70.6  943.06    87.3  926.75    90.7  924.74   100.5  922.03
   104.1  919.16   110.8  912.27  115.56  909.22   120.9  907.82   130.9   907.5
  148.72909.2195   164.5  911.54   181.2  912.59   194.7  914.37   234.9  916.47
   255.4  918.81   294.1  929.89   325.5  933.46   342.2  934.52     359  937.25
   372.4  942.67   382.5   944.6   389.2  947.59   395.9  949.34   409.9  955.42
#Mann= 3 ,-1,0
       0      .1       0  115.56    .045       0  148.72      .1       0
Bank Sta=115.56,148.72
XS Rating Curve= 0 ,0
Exp/Cntr(USF)=0,0
Exp/Cntr=0.3,0.1

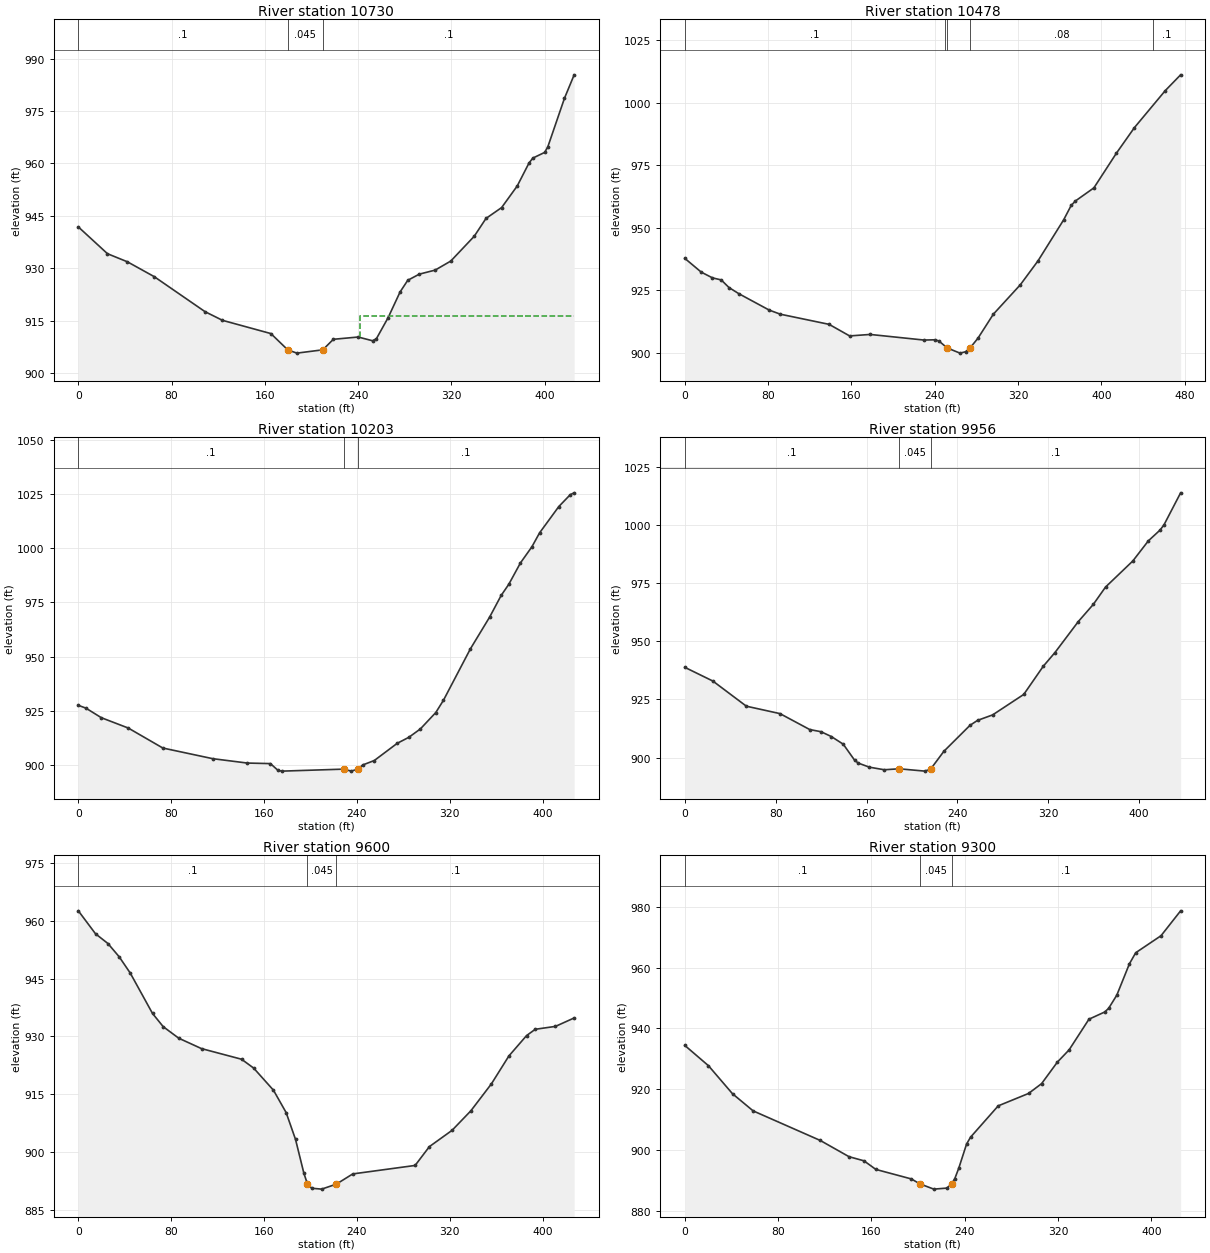
Type RM Length L Ch R = 1 ,10730   ,233.1,251.5,266.9
XS GIS Cut Line= 3
1671476.95610222539284.699237535 1671404.3103457 539404.93443005
 1671463.6562381539683.390070451
#Sta/Elev= 30
       0  941.79      25  934.12    42.1   931.8    65.1  927.55   108.6  917.54
   123.6  915.05   165.1  911.26  179.56906.6062   187.4  905.66  209.66906.6064
   218.7  909.62     240  910.27   252.3   909.2   255.6  909.78   265.7  915.84
   275.9  923.16   282.5  926.51   292.4  928.27     306  929.43   319.4  932.02
   339.5  939.11   349.6  944.22     363  947.33   376.4  953.52   386.5   960.1
   389.8   961.5   399.9  963.12   402.6   964.7   416.9  978.63   425.2  985.33
#Mann= 3 ,-1,0
       0      .1       0  179.56    .045       0  209.66      .1       0
#XS Ineff= 2 , 0
                          241.16           916.2
Permanent Ineff=
       F       F
Bank Sta=179.56,209.66
XS Rating Curve= 0 ,0
Exp/Cntr(USF)=0,0
Exp/Cntr=0.3,0.1

Type RM Length L Ch R = 1 ,10478   ,270.2,275.4,275.7
XS GIS Cut Line= 2
1671460.09391738539272.0061738741671029.21325558539474.840967253
#Sta/Elev= 30
       0  937.79    15.8  932.28    26.6  929.99      35  929.17    42.4  926.14
      52  923.65      81  917.14    91.7  915.49   138.6  911.43   158.3  906.81
     178   907.4   229.7  905.16   240.6  905.27   244.2  904.74  251.94 902.022
   264.3  899.94   269.6  900.48  273.99902.0208   281.6  905.92   296.3  915.47
   322.3  927.26   339.2  936.77   363.9  953.19   371.1  958.93   375.2  960.71
   392.9  965.93   414.6  979.83   431.9  990.03   461.5 1004.79   476.2 1011.07
#Mann= 5 ,-1,0
       0      .1       0     250     .08       0  251.94    .045       0
  273.99     .08       0     450      .1       0
Bank Sta=251.94,273.99
XS Rating Curve= 0 ,0
Exp/Cntr(USF)=0,0
Exp/Cntr=0.3,0.1

Type RM Length L Ch R = 1 ,10203   ,244.4,246.8,245.9
XS GIS Cut Line= 2
1671380.09088094539101.4703537541670957.05957477539160.707440005
#Sta/Elev= 30
       0  927.54     6.5  926.26    19.8  921.84      43  917.08    72.8  907.86
   115.8  902.95   145.6  900.93   165.5  900.68   172.1  897.53   175.5  897.21
   228.7898.1293   235.1  897.23  240.83898.1096     245  900.04     255   902.1
   274.8  910.05   284.8  912.81   294.7  916.66     308  924.23   314.6  929.89
   337.8  953.58   354.4  968.24   364.3  978.19   370.9  983.35   380.9  993.17
   390.8 1000.63   397.4 1007.04     414 1019.19   423.9 1024.67   427.2  1025.5
#Mann= 3 ,-1,0
       0      .1       0   228.7    .045       0  240.83      .1       0
Bank Sta=228.7,240.83
XS Rating Curve= 0 ,0
Exp/Cntr(USF)=0,0
Exp/Cntr=0.3,0.1

Type RM Length L Ch R = 1 ,9956    ,360.2,356.1,345
XS GIS Cut Line= 3
1671355.70377162538903.1456544761671090.71625371 538899.80943195
1670926.47865892 538949.16196765
#Sta/Elev= 30
       0  938.76    24.7  932.87    54.2  922.06    83.8  918.87     110  912.02
   119.9   911.1     129  909.02   139.5  905.73   149.4  898.92   152.7  897.61
   162.5  895.86   175.6  894.75   188.8  895.16   211.4  894.16   216.4895.0206
   228.1  902.69   251.1  913.85   257.7  915.96     271  918.32   298.4  927.12
   315.6  939.24   325.9  945.13   346.4  958.41   359.6  965.79   370.4  973.25
   394.4  984.45   408.1  993.11   418.3   997.7   421.8  999.93   436.5 1013.74
#Mann= 3 ,-1,0
       0      .1       0   188.8    .045       0   216.4      .1       0
Bank Sta=188.8,216.4
XS Rating Curve= 0 ,0
Exp/Cntr(USF)=0,0
Exp/Cntr=0.3,0.1

Type RM Length L Ch R = 1 ,9600    ,296.8,299.8,305.4
XS GIS Cut Line= 6
1671260.93228035538475.7179654991671186.08433293538521.093530923
1671121.94108851 538560.006182761671036.33364818538611.709819511
1670968.92892735538645.7146727591670891.95696843538690.568585679
#Sta/Elev= 30
       0  962.63    14.8  956.67    25.5  954.14    35.2  950.69    44.7  946.48
    63.9  935.98    73.1  932.55    86.5  929.55   106.1  926.85   140.6  924.09
     151   921.8   168.1  916.04     179  910.24   187.1  903.26   194.3  894.47
   197.4891.6612   201.1  890.59   209.6  890.36  222.28891.6606   236.4  894.31
   290.1  896.51   302.4   901.4   321.9  905.62   338.1  910.69   355.8  917.69
   370.9  924.95   386.1  930.23   393.6  931.87     411  932.62   427.1  934.81
#Mann= 3 ,-1,0
       0      .1       0   197.4    .045       0  222.28      .1       0
Bank Sta=197.4,222.28
XS Rating Curve= 0 ,0
Exp/Cntr(USF)=0,0
Exp/Cntr=0.3,0.1

Type RM Length L Ch R = 1 ,9300    ,298.5,300,301
XS GIS Cut Line= 6
1671107.65535593538292.5752871781671023.84515609538318.105419844
1670951.58677043 538338.304198341670854.57252875538362.558414921
1670781.81184751538380.7489953341670696.92455009 538401.97106576
#Sta/Elev= 30
       0  934.42    20.3  927.75    40.9  918.55    58.6  912.92   116.2   903.2
   140.8  897.88   153.6  896.53   163.8   893.7   194.3  890.57  201.44888.9678
   213.5  887.23   224.7  887.57  228.82 888.968   231.5  890.69   234.9  894.12
   241.6  902.05     245  904.29   268.7  914.57   294.7  918.64   305.9  921.87
   319.4  928.92   329.5  932.96   346.5  943.02     360  945.39   363.4   946.6
   370.4  950.93   381.2  961.22   386.6  964.85   408.3  970.44   425.1  978.61
#Mann= 3 ,-1,0
       0      .1       0  201.44    .045       0  228.82      .1       0
Bank Sta=201.44,228.82
XS Rating Curve= 0 ,0
Exp/Cntr(USF)=0,0
Exp/Cntr=0.3,0.1

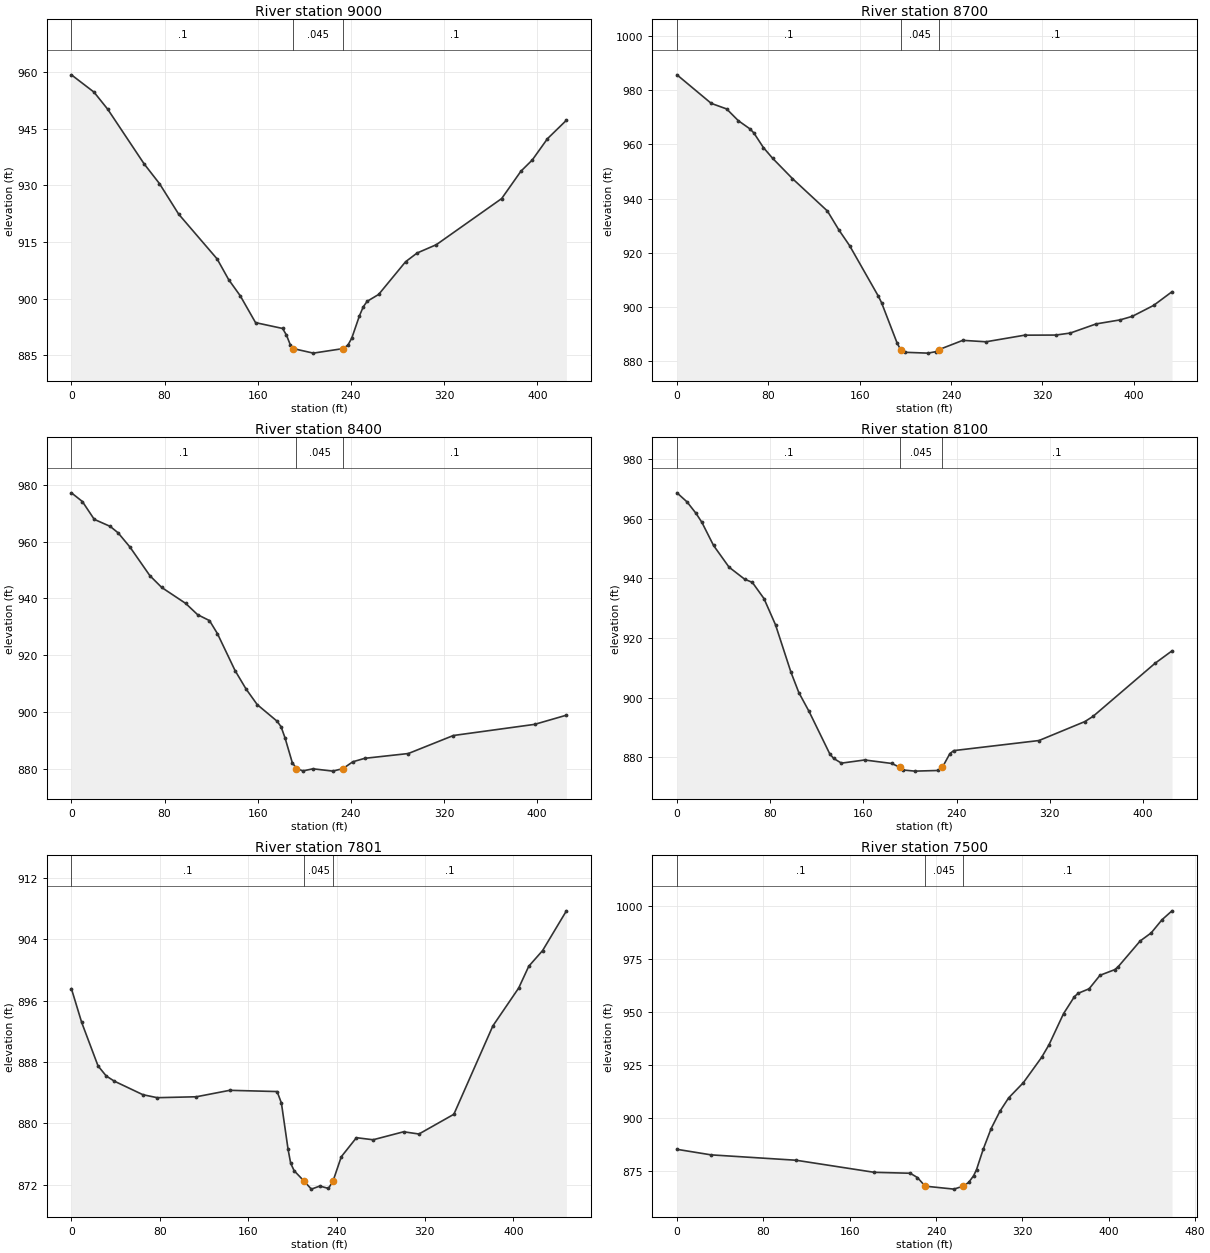
Type RM Length L Ch R = 1 ,9000    ,301.6,300,297.4
XS GIS Cut Line= 6
1671087.83059242 538029.188018681671000.91639617538039.294297665
1670926.41818559538047.9573380951670827.08767559538059.508496091
1670752.53401892538067.6918786761670665.32126684538075.233858332
#Sta/Elev= 30
       0  959.26    19.4  954.68    31.2  950.14    62.4   935.7    75.6  930.47
    92.1  922.38   125.1  910.53     135  905.06   144.9   900.8   158.1  893.67
   181.3  892.13   184.6  890.39   187.9  887.82  190.45   886.8   207.7   885.6
  233.22886.8005   237.4  887.73   240.7  889.57   247.3  895.49   250.6  897.87
   253.9  899.31   263.8  901.14   286.9  909.79   296.8   912.1   313.3   914.3
   369.4  926.51   385.9  933.74   395.7  936.73   408.7  942.35     425  947.24
#Mann= 3 ,-1,0
       0      .1       0  190.45    .045       0  233.22      .1       0
Bank Sta=190.45,233.22
XS Rating Curve= 0 ,0
Exp/Cntr(USF)=0,0
Exp/Cntr=0.3,0.1

Type RM Length L Ch R = 1 ,8700    ,318,300.5,280.9
XS GIS Cut Line= 6
1671061.45761368537702.2949716751670976.75797993 537724.25457342
1670904.15838759537743.0770423411670807.35871242537768.174105003
1670732.93300825537787.6645515861670645.89479651537823.258312419
#Sta/Elev= 30
       0   985.7      30  975.16    43.5   973.1    53.7  968.77    63.9  965.74
    67.3  964.25    75.7  958.83    83.8  954.86   101.1  947.39   131.7  935.43
   141.8  928.41   151.1  922.67   176.4  903.92   179.1  901.61   192.7  886.74
  195.83884.2199   199.4  883.25   219.8  882.94   226.6  883.47  229.27884.2168
   250.3  887.66   270.6  887.13   304.5  889.57   331.7  889.61   344.4  890.35
   367.1  893.73     388  895.21   398.7  896.52   417.4  900.56   433.5  905.61
#Mann= 3 ,-1,0
       0      .1       0  195.83    .045       0  229.27      .1       0
Bank Sta=195.83,229.27
XS Rating Curve= 0 ,0
Exp/Cntr(USF)=0,0
Exp/Cntr=0.3,0.1

Type RM Length L Ch R = 1 ,8400    ,308.4,299.5,291
XS GIS Cut Line= 6
 1670697.2923315 537362.917041511670673.11488642537447.010705337
1670652.39183076537519.0906136781670623.88532609537614.945736915
1670599.62192318537686.0082588341670570.66397583537768.727253512
#Sta/Elev= 30
       0  977.28     9.4  974.22    19.6  967.93    33.3  965.44    40.1  963.17
    50.3  958.14    67.4  948.05    77.6  943.88    98.1  938.28   108.4  934.29
   118.6   932.2   125.4  927.62   140.6  914.55     150  908.07   159.6  902.56
   176.7  896.69   180.1  894.74   183.5   890.8   189.7  882.11  193.29880.0008
   198.9  879.17   207.5  879.91   224.6  879.09  233.33880.0023   241.7  882.39
     252  883.61   289.4   885.3   328.1  891.66   397.9  895.59   425.2  898.83
#Mann= 3 ,-1,0
       0      .1       0  193.29    .045       0  233.33      .1       0
Bank Sta=193.29,233.33
XS Rating Curve= 0 ,0
Exp/Cntr(USF)=0,0
Exp/Cntr=0.3,0.1

Type RM Length L Ch R = 1 ,8100    ,306.6,299.3,283.5
XS GIS Cut Line= 6
1670306.45682709537347.4794083391670320.73796651537433.806335419
1670332.97973992537507.8006100061670349.30188575537606.459533423
1670361.54365918537680.4534799161670375.82578284537766.780078918
#Sta/Elev= 30
       0  968.64     8.6  965.61    16.4  961.73    21.4  958.72    31.4  950.98
    44.7  943.71      58   939.7    64.7   938.6    74.7  933.17    84.6  924.37
    97.9  908.42   104.6  901.66   113.4  895.32   131.2  881.08   134.5  879.57
   141.2  877.99   161.1  879.05   184.4  877.88  191.46 876.562   194.4  875.68
   204.3  875.31   224.3  875.53  227.81876.5602   234.3  881.19   237.6  882.19
   310.8  885.57   350.2  891.93   357.3   893.7   410.5  911.49     425  915.64
#Mann= 3 ,-1,0
       0      .1       0  191.46    .045       0  227.81      .1       0
Bank Sta=191.46,227.81
XS Rating Curve= 0 ,0
Exp/Cntr(USF)=0,0
Exp/Cntr=0.3,0.1

Type RM Length L Ch R = 1 ,7801    ,280.9,300.7,320.8
XS GIS Cut Line= 6
1669933.85455392537481.7252028441669977.92369151537567.130871922
1670041.92848475537606.2216730121670126.73080859 537659.23698692
 1670181.8350291537715.0774264191670242.92217726537792.347285002
#Sta/Elev= 30
       0  897.56     9.3  893.16    24.1   887.5    31.5  886.19    38.9  885.51
    64.7  883.75    77.7  883.36   113.1  883.48   143.3  884.32   186.2  884.16
   190.1  882.66   196.1  876.65   198.5  874.81   201.7  873.83  210.41872.5276
   217.2  871.45   224.9  871.85   232.7  871.54  236.88872.5271   244.3  875.67
     258  878.15   273.1  877.88   300.7  878.92   314.6  878.63   346.2   881.2
   381.5  892.71   404.9  897.65     414  900.48   426.5  902.52   448.1   907.7
#Mann= 3 ,-1,0
       0      .1       0  210.41    .045       0  236.88      .1       0
Bank Sta=210.41,236.88
XS Rating Curve= 0 ,0
Exp/Cntr(USF)=0,0
Exp/Cntr=0.3,0.1

Type RM Length L Ch R = 1 ,7500    ,223.6,230.2,236.3
XS GIS Cut Line= 6
1669892.33429575537514.1664109231669894.88350326537632.013616174
 1669891.2608071537710.207357422  1669867.008559 537807.22225526
  1669848.819619537879.9832645951669827.43941243537964.817084417
#Sta/Elev= 30
       0  885.31    31.6   882.7   110.4  880.16   182.7  874.47   216.1  874.03
   222.8  871.98   229.9867.9457   256.6  866.54  265.01867.9441   270.2  869.68
   274.8  872.85   277.5  875.73   283.7  885.36     291  895.07   299.1  903.19
   307.2  909.54   320.9  916.76   337.8  928.68   344.6  934.59   358.1  949.29
   368.2  957.33   371.6  958.89   381.8  961.03   391.9   967.4   405.5  970.05
   408.8  971.48   429.1  983.58   439.3  987.38   449.4  993.63   458.6   997.8
#Mann= 3 ,-1,0
       0      .1       0   229.9    .045       0  265.01      .1       0
Bank Sta=229.9,265.01
XS Rating Curve= 0 ,0
Exp/Cntr(USF)=0,0
Exp/Cntr=0.3,0.1

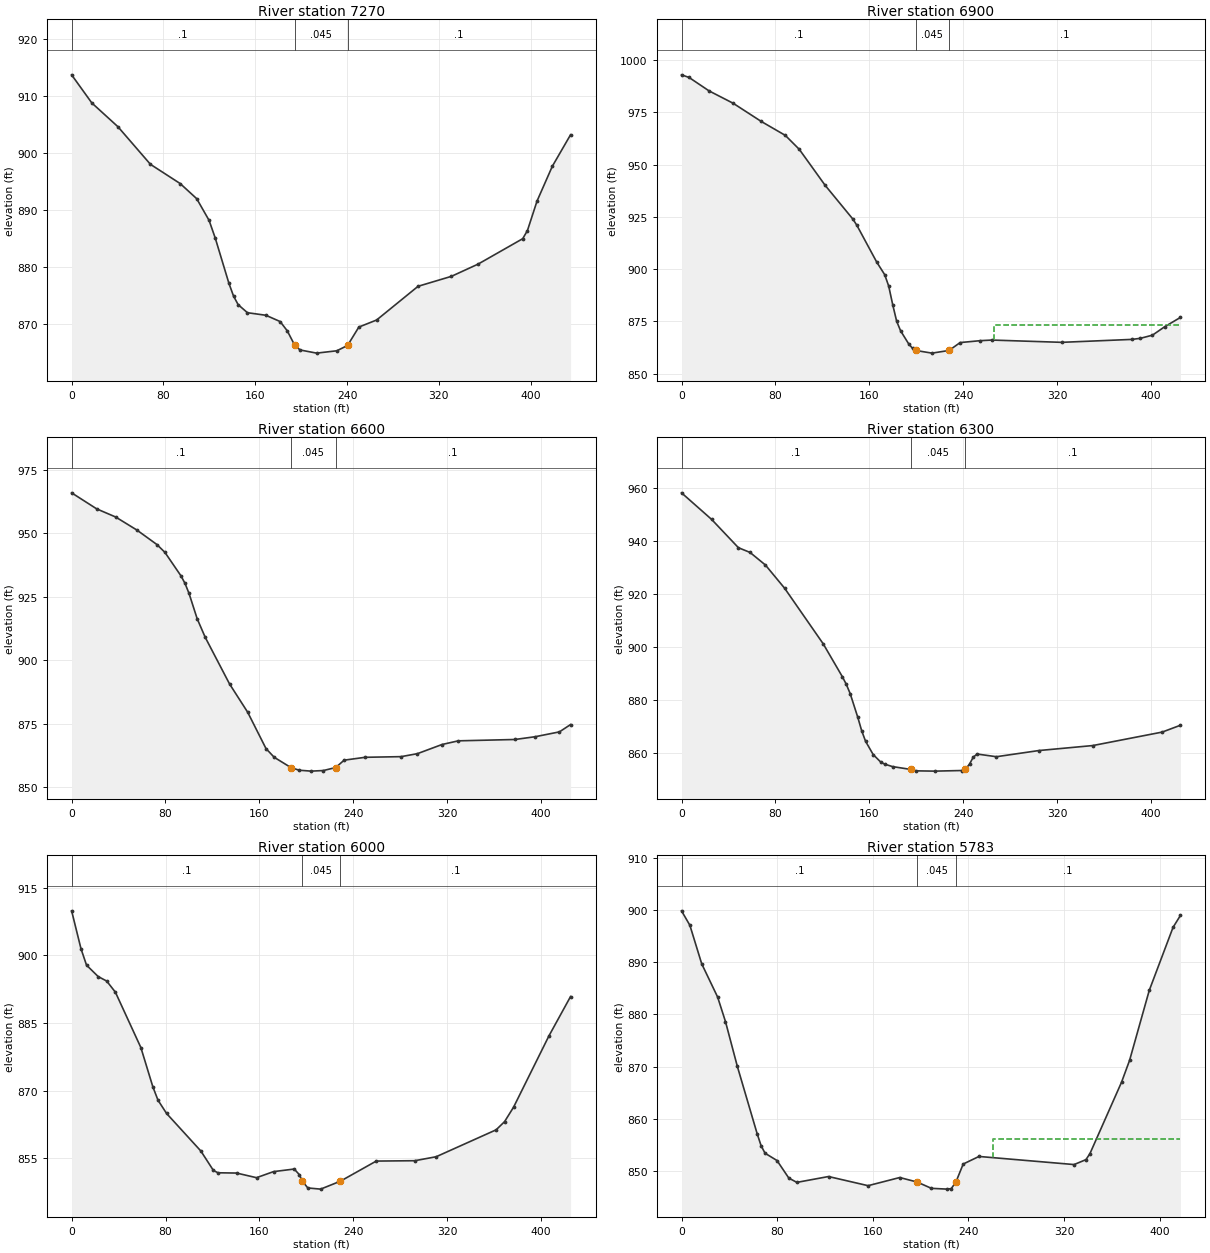
Type RM Length L Ch R = 1 ,7270    ,373.1,369.8,364
XS GIS Cut Line= 3
1669822.16514476537453.6222406771669630.81519156537723.701693169
1669601.09229338537823.111200306
#Sta/Elev= 30
       0   913.7    17.6  908.77    40.3  904.61    68.7     898    94.6  894.63
     109  891.98   119.8  888.17   125.2  885.05   137.1  877.12   141.1   874.9
   145.1   873.4   153.2  871.98   169.3  871.53   181.7  870.43   187.9  868.81
  194.51866.2341   199.2  865.44   213.5  864.89   231.1   865.3  240.47866.2353
   250.3  869.46   265.8   870.7   301.9  876.61     331  878.36   354.2   880.5
   393.1  884.96   397.2  886.38   405.6  891.57   418.9  897.66   434.8  903.19
#Mann= 3 ,-1,0
       0      .1       0  194.51    .045       0  240.47      .1       0
Bank Sta=194.51,240.47
XS Rating Curve= 0 ,0
Exp/Cntr(USF)=0,0
Exp/Cntr=0.3,0.1

Type RM Length L Ch R = 1 ,6900    ,312.5,300,291.3
XS GIS Cut Line= 6
 1669470.8443251537198.4505069261669446.15244535537282.453291669
  1669427.261407537355.0361517521669402.52326751537451.927690253
1669383.97048309537524.5968362541669356.15656234537607.797785342
#Sta/Elev= 30
       0  992.88     6.4  991.63    23.5  985.19      44  979.29      68  970.58
    88.5  963.92   100.4  957.24   122.4  940.06   146.1  923.87   149.5   920.9
   166.4  903.33   173.2  897.31   176.6  891.87     180  883.02   183.4  875.01
   186.8  870.42   193.5  864.36   196.9  862.09  199.58  861.09   213.5  859.81
  228.04861.0903   237.5  864.86   254.5  865.76   264.6  866.06   324.1  864.97
   384.1  866.38   391.1  866.89   401.4  868.39   411.8  872.41   425.3  876.89
#Mann= 3 ,-1,0
       0      .1       0  199.58    .045       0  228.04      .1       0
#XS Ineff= 2 , 0
                          266.43           873.3
Permanent Ineff=
       F       F
Bank Sta=199.58,228.04
XS Rating Curve= 0 ,0
Exp/Cntr(USF)=0,0
Exp/Cntr=0.3,0.1

Type RM Length L Ch R = 1 ,6600    ,291.6,300,306.4
XS GIS Cut Line= 6
1669057.83629283537184.0194334241669082.23388185537268.239081249
1669105.54059376537339.5689910951669139.71539417537433.548133835
1669164.75537033537504.2474675031669191.30124901537587.699728429
#Sta/Elev= 30
       0  965.95    21.4  959.62    37.5  956.43    55.6  951.29    72.7  945.57
    79.5   942.5    93.2  933.23    96.7  930.21   100.1  926.28     107  916.35
   113.9  908.98   134.6  890.63   150.1  879.45   165.7  865.13   172.7   861.7
  186.87857.6744   193.9  856.61   204.1  856.25   214.6  856.48  225.13857.6735
   232.3  860.57   250.2   861.7   280.9  861.96   294.8  863.14   315.7  866.74
   329.6  868.19   377.9  868.72   395.1  869.81   415.8  871.72   425.3  874.61
#Mann= 3 ,-1,0
       0      .1       0  186.87    .045       0  225.13      .1       0
Bank Sta=186.87,225.13
XS Rating Curve= 0 ,0
Exp/Cntr(USF)=0,0
Exp/Cntr=0.3,0.1

Type RM Length L Ch R = 1 ,6300    ,307.1,300,290.6
XS GIS Cut Line= 6
1668826.25309458537205.2917005871668826.25309458537292.791525587
1668826.25309458537367.7917036711668826.25309458537467.791831762
1668826.25309458537542.791681752 1668823.2393211537630.291506752
#Sta/Elev= 30
       0  958.25    25.6  948.22    48.5  937.49    58.4  935.71    71.5  930.95
    87.9  922.14   120.7  901.17   137.1  888.67   140.4  885.83   143.7  882.33
   150.2  873.34   153.5  868.29   156.8  864.32   163.3  859.28   169.9  856.37
   173.2  855.65   179.8  854.73  195.09853.6783   199.4  853.13   215.8  853.02
   238.8  853.25  241.81853.6786   245.4   855.7   248.6  858.33   251.9  859.48
   268.3  858.47   304.4   860.8   350.4  862.69   409.5  867.78   425.1  870.37
#Mann= 3 ,-1,0
       0      .1       0  195.09    .045       0  241.81      .1       0
Bank Sta=195.09,241.81
XS Rating Curve= 0 ,0
Exp/Cntr(USF)=0,0
Exp/Cntr=0.3,0.1

Type RM Length L Ch R = 1 ,6000    ,207.4,217.2,226.6
XS GIS Cut Line= 6
1668443.95694317537276.1163620951668482.06775934537354.880640253
1668514.73468876537422.3926443461668558.29168826537512.408212334
1668590.95861767537579.9202164261668629.07074617537658.683838427
#Sta/Elev= 30
       0  909.91       8  901.48    12.7  897.85    22.6  895.32    29.9  894.31
    37.3  891.84      59  879.54    69.2  870.83    73.6  867.85    80.9  864.91
   110.1  856.57   120.8  852.25   124.7  851.74   140.5  851.68   157.5  850.65
     172     852   189.6  852.57   193.9  851.35  196.55849.8729   201.2  848.37
   212.1  848.11  228.94849.8708   259.5  854.34   292.3  854.42   310.5   855.3
   361.6  861.28   368.8   863.1   376.5  866.33   406.6  882.15     425  890.88
#Mann= 3 ,-1,0
       0      .1       0  196.55    .045       0  228.94      .1       0
Bank Sta=196.55,228.94
XS Rating Curve= 0 ,0
Exp/Cntr(USF)=0,0
Exp/Cntr=0.3,0.1

Type RM Length L Ch R = 1 ,5783    ,238,241.1,232.3
XS GIS Cut Line= 2
1668356.30816834537279.7242944991668297.00539947537692.944137953
#Sta/Elev= 30
       0  899.83       7  897.06    16.9  889.69    30.2  883.34    36.8  878.63
    46.7  870.08    63.3  857.18    66.6  854.89    69.9  853.46    79.9  852.06
    89.8   848.7    96.5  847.88     123     849   156.1  847.25   182.6  848.81
   197.2847.9433   209.1  846.74   222.4  846.59   225.7  846.69  229.58847.9383
   235.7  851.39   248.9  852.84   328.5  851.29   338.4  852.23   341.7  853.36
   368.2  867.05   374.9  871.21   391.4  884.62   411.3  896.67   417.5  898.96
#Mann= 3 ,-1,0
       0      .1       0   197.2    .045       0  229.58      .1       0
#XS Ineff= 2 , 0
                          260.65          856.09
Permanent Ineff=
       F       F
Bank Sta=197.2,229.58
XS Rating Curve= 0 ,0
Exp/Cntr(USF)=0,0
Exp/Cntr=0.3,0.1

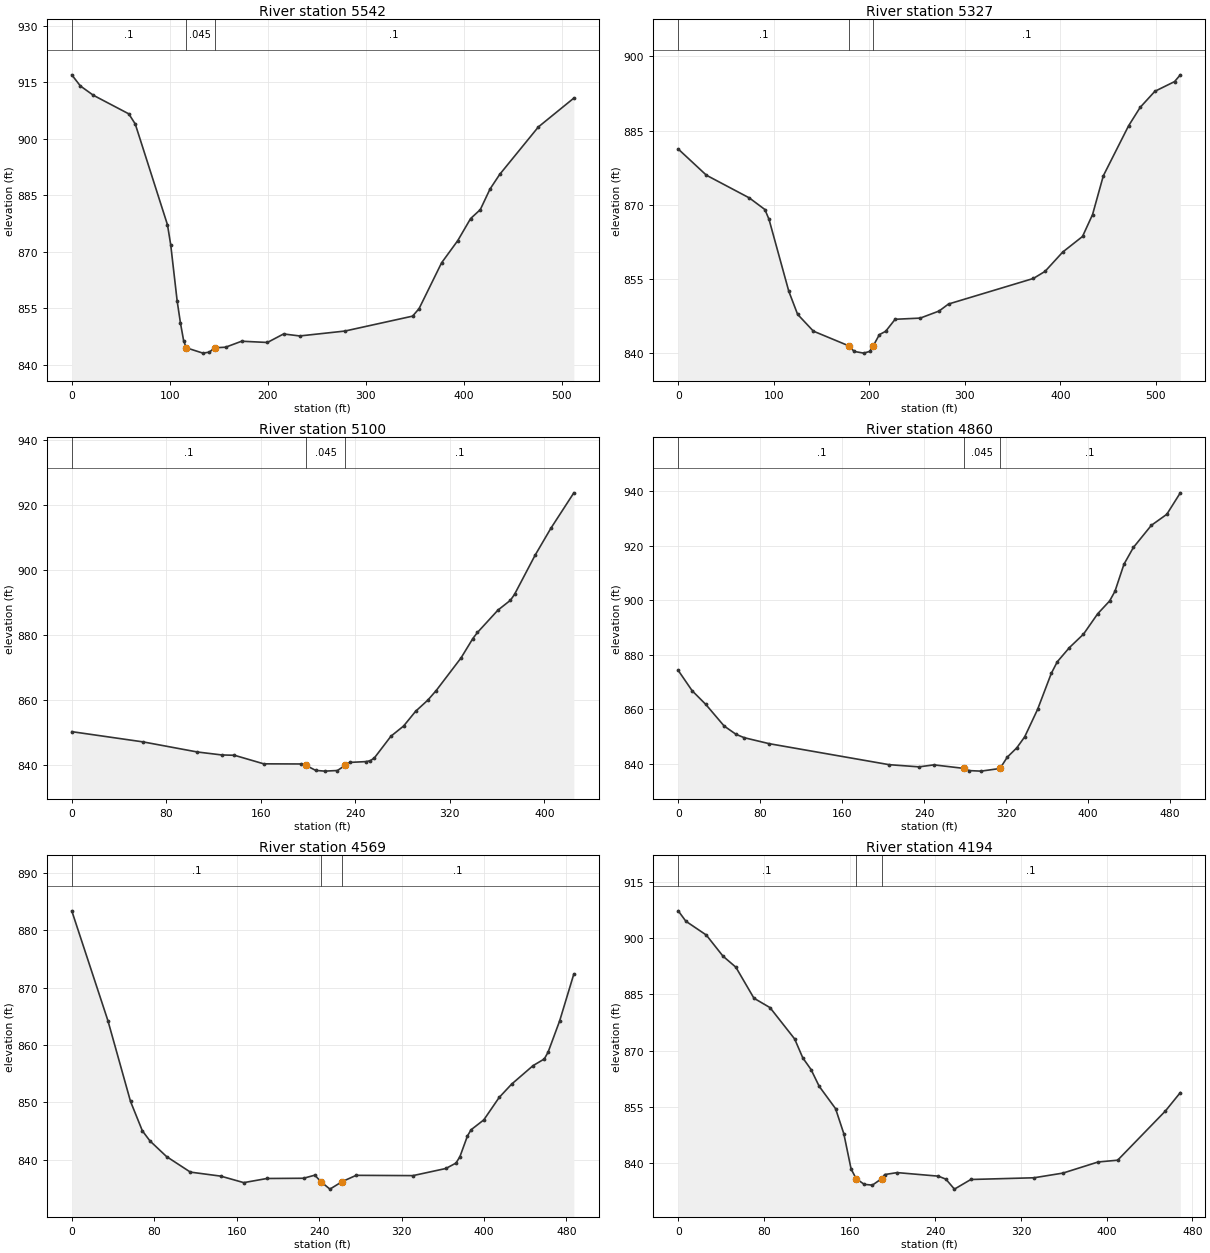
Type RM Length L Ch R = 1 ,5542    ,210.7,214.4,213.7
XS GIS Cut Line= 2
1668124.72966049537254.8609742811668166.67749861537765.637591421
#Sta/Elev= 30
       0  916.95     8.8  913.99      22  911.53    58.2  906.59    64.8   903.9
    97.7  877.13     101  871.83   107.6  856.86   110.9  851.13   114.2  846.35
   116.9844.4861   133.9  843.07   140.5  843.34  145.76844.4876     157  844.64
   173.4  846.23   199.7   845.9   216.2  848.16   232.7  847.63   278.8  848.93
   347.9  852.89   354.5  854.88   377.5  867.05     394  872.94   407.1  878.79
     417  881.16   426.9  886.62   436.8  890.51   476.3  903.12   512.5  910.77
#Mann= 3 ,-1,0
       0      .1       0   116.9    .045       0  145.76      .1       0
Bank Sta=116.9,145.76
XS Rating Curve= 0 ,0
Exp/Cntr(USF)=0,0
Exp/Cntr=0.3,0.1

Type RM Length L Ch R = 1 ,5327    ,223.3,227.3,230.5
XS GIS Cut Line= 4
 1667975.5294486537255.235065324 1667943.3669486537354.795529809
1667923.62678949537624.9889577161667878.16248052537768.105782284
#Sta/Elev= 30
       0  881.25    29.5  875.95    74.4  871.36    90.7  869.01      95  867.05
   115.8  852.44     125  847.79   141.5  844.39  178.33 841.434   184.3  840.28
   194.2  839.94   200.7   840.3  204.24841.4362   210.6  843.68   217.2  844.36
   227.1  846.79   253.4  847.03   273.1  848.46     283  849.88   371.8  855.05
   384.1  856.49   402.6   860.4   423.3  863.55   433.8  867.98   445.1  875.84
   471.5  885.94   483.7  889.69   499.1  892.94   519.7   894.9   525.7  896.27
#Mann= 3 ,-1,0
       0      .1       0  178.33    .045       0  204.24      .1       0
Bank Sta=178.33,204.24
XS Rating Curve= 0 ,0
Exp/Cntr(USF)=0,0
Exp/Cntr=0.3,0.1

Type RM Length L Ch R = 1 ,5100    ,234.3,240.5,247.2
XS GIS Cut Line= 6
1667794.48055184537176.759933501 1667764.8415035537259.087196678
1667739.43768293537329.6536565871667705.56504726537423.742379174
 1667680.1608986537494.3088390831667650.52349067537576.636758417
#Sta/Elev= 30
       0  850.29    60.4  847.14   106.3  844.04     127  843.13   137.7  843.03
   162.5   840.4   193.7  840.36  198.26839.9248   206.5  838.38   214.2  838.16
   224.9  838.35  231.35839.9232   235.3  840.84   249.3  841.09   252.8  841.38
   256.2  842.24   270.2   848.9   280.9  852.02   291.1  856.56   301.4  859.98
   308.5  862.93   329.5  872.94   339.5   878.9   343.4  880.76   360.8  887.65
   371.3  890.65   374.8  892.48   392.2   904.5   405.5  912.75     425  923.67
#Mann= 3 ,-1,0
       0      .1       0  198.26    .045       0  231.35      .1       0
Bank Sta=198.26,231.35
XS Rating Curve= 0 ,0
Exp/Cntr(USF)=0,0
Exp/Cntr=0.3,0.1

Type RM Length L Ch R = 1 ,4860    ,284.8,290.8,294.9
XS GIS Cut Line= 2
 1667735.9671536537017.3928414411667406.14288974537379.741449945
#Sta/Elev= 30
       0   874.2    13.6  866.73    26.9  861.71    44.8  853.78    56.4  850.73
    64.4  849.49    88.8  847.29   205.8  839.58     235  838.78   249.6  839.51
   279.3  838.19   283.8   837.4   295.6  837.21     314 838.185   321.2  842.37
   330.4  845.76   338.1  849.79   350.7  859.88   364.1  873.13   369.9  877.36
   381.8   882.6   395.5  887.52   409.4  895.03     421  899.71   426.2  903.24
     435   913.2   444.2  919.36   461.7  927.48   476.8  931.54     490  939.43
#Mann= 3 ,-1,0
       0      .1       0   279.3    .045       0     314      .1       0
Bank Sta=279.3,314
XS Rating Curve= 0 ,0
Exp/Cntr(USF)=0,0
Exp/Cntr=0.3,0.1

Type RM Length L Ch R = 1 ,4569    ,382.3,374.6,368.9
XS GIS Cut Line= 2
1667592.94032391536895.2383226191667154.98119524 537108.74218724
#Sta/Elev= 30
       0  883.34    35.1  864.22      57  850.19    68.5  845.07    75.9  843.31
      92  840.59   115.1  837.89   144.6  837.19   166.9  836.06   189.4  836.78
   224.9  836.82   235.9  837.36  241.62836.2407   250.5  834.93   262.4  836.24
     276  837.33   331.1  837.28     363  838.52   372.8  839.46   376.6  840.55
     384   844.2   387.5  845.26   399.8  846.97   414.7  850.87   426.8  853.19
   447.6  856.41   458.5  857.57   462.2  858.75   473.4  864.18   487.2  872.36
#Mann= 3 ,-1,0
       0      .1       0  241.62    .045       0   262.4      .1       0
Bank Sta=241.62,262.4
XS Rating Curve= 0 ,0
Exp/Cntr(USF)=0,0
Exp/Cntr=0.3,0.1

Type RM Length L Ch R = 1 ,4194    ,291.5,292.8,294.2
XS GIS Cut Line= 6
1667325.51704319536537.3434462031667280.41116227536612.321314626
1667241.82495336536676.6341781251667190.37623737536762.383678533
1667151.78937228536826.6958858751667062.35100266536922.801070299
#Sta/Elev= 30
       0   907.3     7.1  904.53    26.2  900.84    41.8   895.2    53.8  892.26
    70.7  883.98    85.7  881.47   108.7  873.11   116.3  868.06     124  864.95
   131.6  860.48   146.9  854.51   154.6  847.83   161.4  838.42  166.11835.8325
   173.7   834.3   181.3   834.1  189.92835.8231   192.8  836.92   204.4  837.44
   242.9  836.49   249.9  835.69   257.9  833.03   273.2   835.6   332.2  836.06
   359.2  837.31   392.1  840.28   410.3  840.75   454.9  853.89   468.8  858.79
#Mann= 3 ,-1,0
       0      .1       0  166.11    .045       0  189.92      .1       0
Bank Sta=166.11,189.92
XS Rating Curve= 0 ,0
Exp/Cntr(USF)=0,0
Exp/Cntr=0.3,0.1