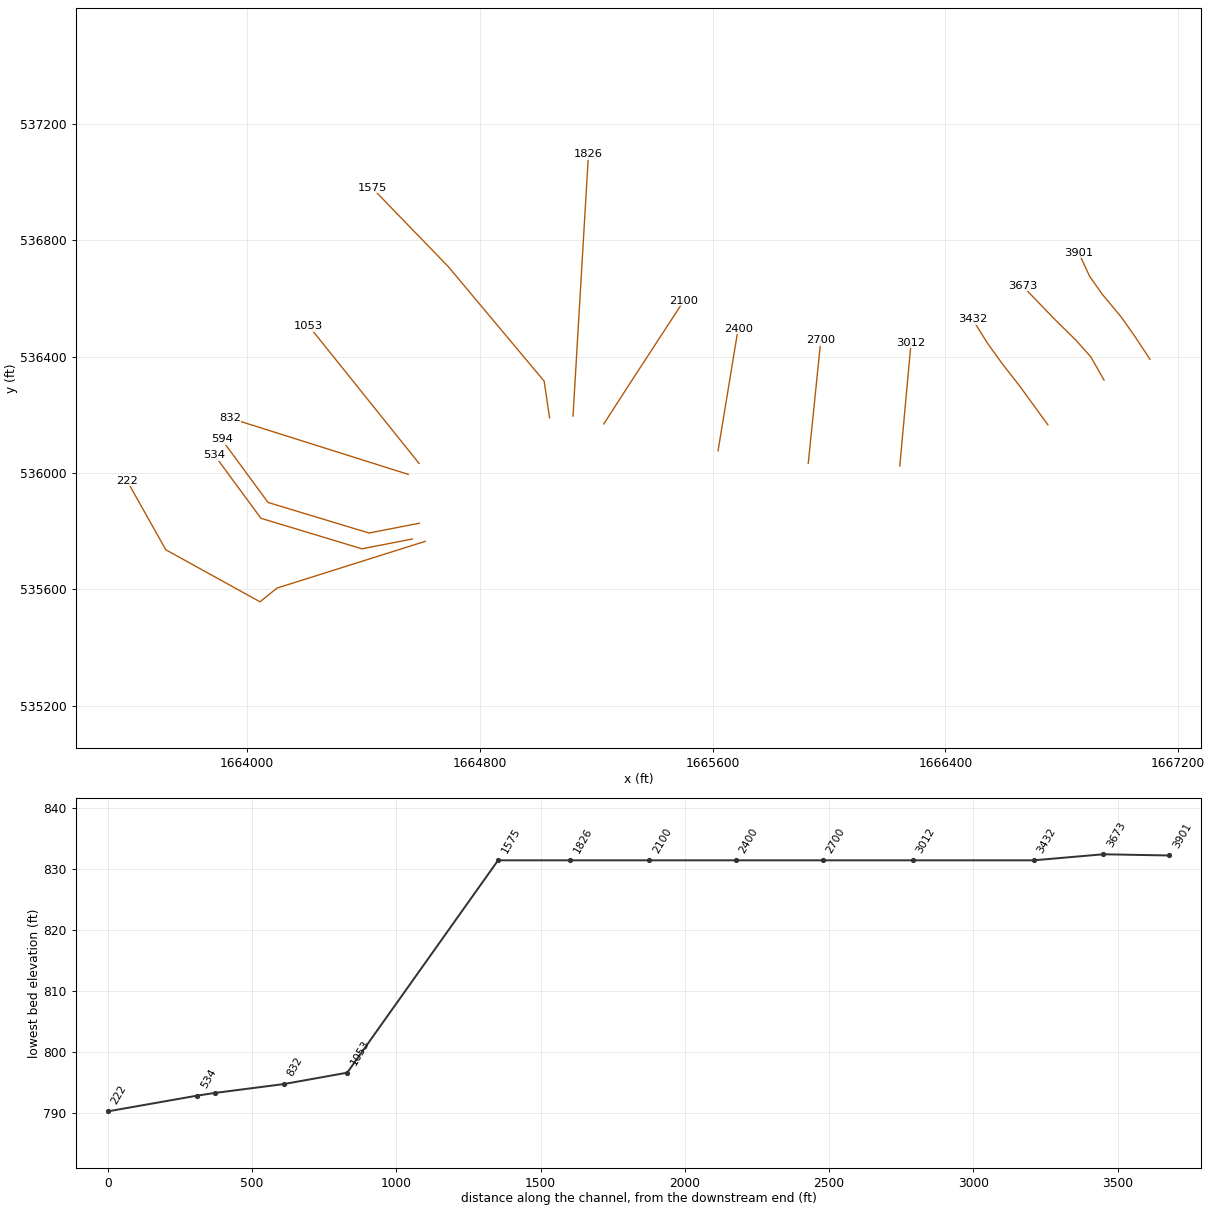
HEC-RAS study TurkeyRn.prj: TurkeyRn

--- TurkeyRn.g01 (geometry) --- (continued)

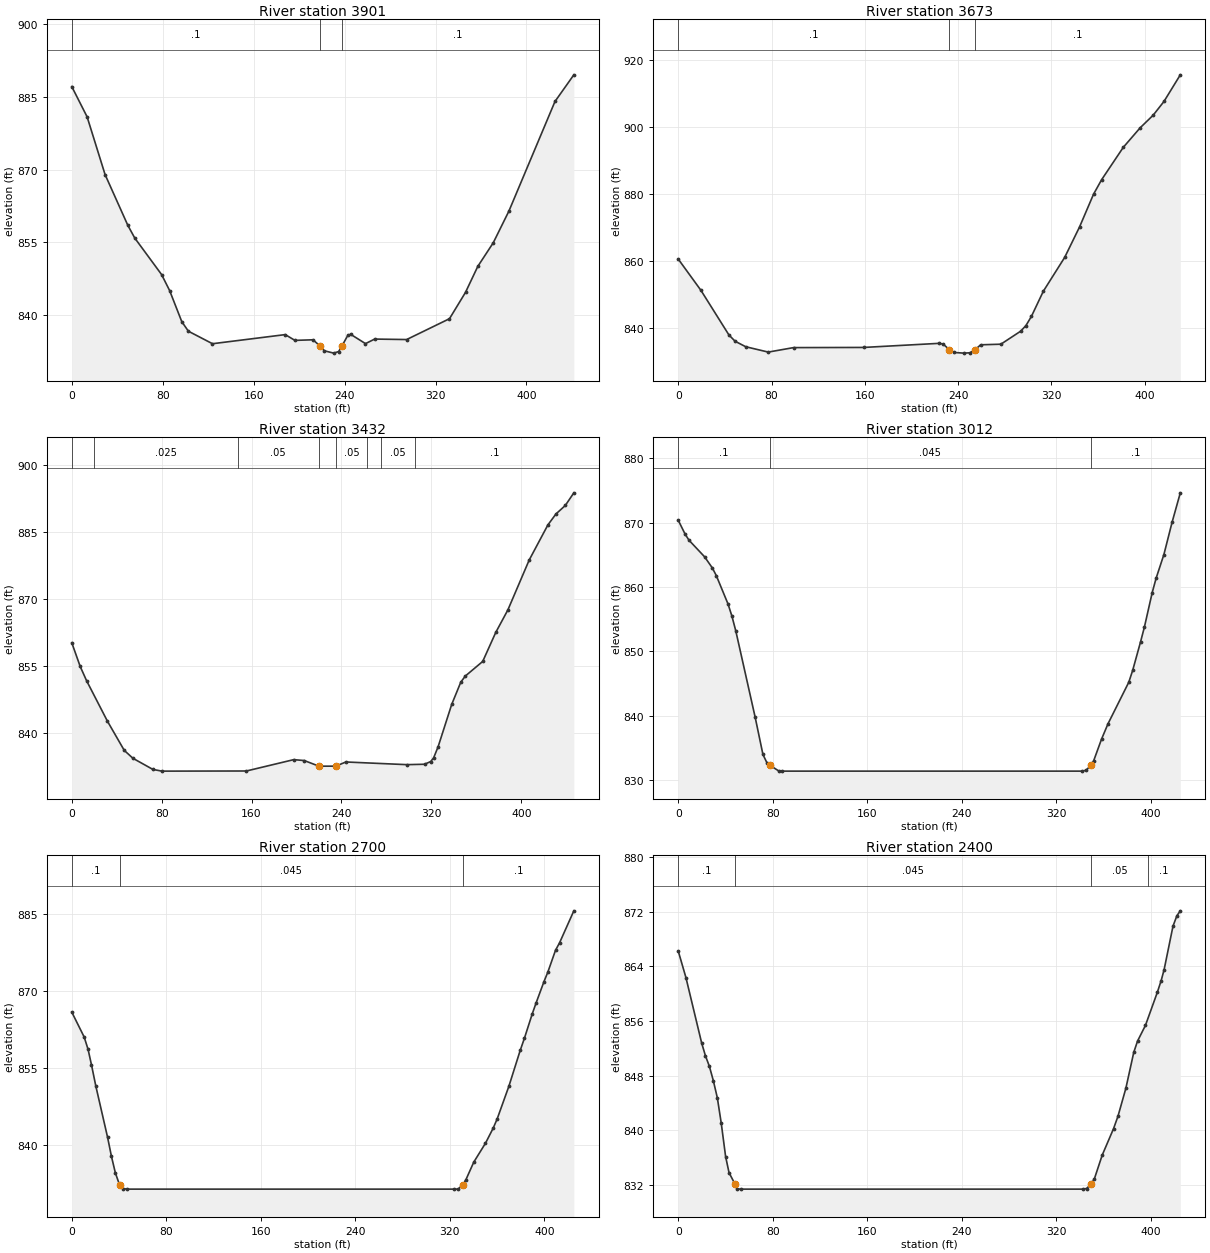
Type RM Length L Ch R = 1 ,3901    ,221.7,228.3,225.6
XS GIS Cut Line= 6
1667102.93895592536390.6762038321667051.65296926536468.386678338
1667004.63797143536535.1490119991666938.97012375536613.991702095
1666895.73661442536675.4157918391666858.18288375536756.341811091
#Sta/Elev= 30
       0  887.15    13.5   880.9    29.3     869    49.3  858.54    55.4  855.91
      79  848.38    86.1  845.07    96.8  838.65   102.6  836.69   123.8  834.11
   187.8  835.99   196.3   834.8   212.2  834.92  217.99833.7339   222.2  832.65
   230.5  832.17   234.8   832.5   237.9  833.74     243  835.89   245.5  836.03
   258.4  834.13   266.5  835.07   294.6  834.97   332.3  839.27   346.4  844.71
   357.2  850.06   370.8  854.93   384.6  861.48   425.1  884.07   441.7  889.57
#Mann= 3 ,-1,0
       0      .1       0  217.99    .045       0   237.9      .1       0
Bank Sta=217.99,237.9
XS Rating Curve= 0 ,0
Exp/Cntr(USF)=0,0
Exp/Cntr=0.3,0.1

Type RM Length L Ch R = 1 ,3673    ,242.5,241.3,240.2
XS GIS Cut Line= 6
1666945.15005047536319.071749929 1666899.6258633536398.842259679
1666848.94617463536455.7745605141666777.56869273536525.865299601
1666725.50842939536579.8533805941666664.77134614536642.839475099
#Sta/Elev= 30
       0   860.5    19.5  851.13    43.5  837.79    48.8  835.92    57.9  834.28
    77.2  832.68    98.9  834.02     159  834.07     224   835.3   227.2  835.08
  232.52833.4088   236.4  832.57   244.9  832.37   250.2  832.47  254.49833.3881
   259.4  834.86   276.7  835.04   293.6  838.91   298.2  840.61   302.9  843.35
   313.1  850.87   331.4  860.98   344.2  870.12   356.2  879.91   363.1  884.23
   381.7  893.92   396.2  899.77   407.3  903.52   416.6  907.64   430.6   915.6
#Mann= 3 ,-1,0
       0      .1       0  232.52    .045       0  254.49      .1       0
Bank Sta=232.52,254.49
XS Rating Curve= 0 ,0
Exp/Cntr(USF)=0,0
Exp/Cntr=0.3,0.1

Type RM Length L Ch R = 1 ,3432    ,474.7,419.9,376.9
XS GIS Cut Line= 6
1666752.22936363536165.2227869441666700.76424347536235.986753028
1666656.65114273536296.6421435291666593.46262081536377.788962867
1666544.36987123536446.0808210341666492.83618164536528.677768704
#Sta/Elev= 30
       0  860.14     7.5  854.82    13.2  851.62    31.7  842.58    46.7  836.03
    54.4  834.26    72.2  831.76    80.2  831.38   155.4  831.41   197.5  833.95
   206.9  833.75  219.96832.4882  235.05832.4946   243.9  833.43   298.2  832.83
   313.9  832.92   319.4  833.52     322  834.34     326  836.83   338.1  846.32
   346.2  851.31   350.2  852.67   365.7  855.95   377.3  862.44   388.1  867.49
   407.1  878.68   423.7  886.52   430.9  888.98   439.2  890.88   446.8  893.71
#Mann= 8 ,-1,0
       0      .1       0      20    .025       0   147.5     .05       0
  219.96    .045       0  235.05     .05       0   262.5      .1       0
  275.35     .05       0  305.35      .1       0
Bank Sta=219.96,235.05
XS Rating Curve= 0 ,0
Exp/Cntr(USF)=0,0
Exp/Cntr=0.3,0.1

Type RM Length L Ch R = 1 ,3012    ,318.9,311.8,313.1
XS GIS Cut Line= 6
  1666243.220997536024.2730092871666251.19834326536111.408333706
1666258.03592801536186.0961764621666267.15270768536285.679638701
1666273.99029243536360.3674814571666281.96763867536447.502805876
#Sta/Elev= 30
       0  870.36     5.8  868.21     9.1  867.26    22.3  864.68    28.9  862.94
    32.2  861.77    42.1  857.37    45.4  855.49    48.7  853.18    65.1  839.77
    71.7  833.97      75   832.7   77.42832.3073    84.9  831.43    88.2  831.38
   341.9  831.38   345.2  831.51  349.41832.3077   351.7  833.01   358.3  836.34
   363.8  838.74   381.4   845.2   384.7  847.05   391.3  851.43   394.6  853.76
   401.2  859.11   404.5  861.34   411.1  865.03   418.1  870.09     425  874.62
#Mann= 3 ,-1,0
       0      .1       0   77.42    .045       0  349.41      .1       0
Bank Sta=77.42,349.41
XS Rating Curve= 0 ,0
Exp/Cntr(USF)=0,0
Exp/Cntr=0.3,0.1

Type RM Length L Ch R = 1 ,2700    ,310.4,300,292.9
XS GIS Cut Line= 6
 1665928.6289686536032.7080877571665937.51149675536119.756142005
1665945.12467051536194.368525594  1665955.276225536293.851922423
1665962.88972685536368.4646340911665971.77192692536455.512688339
#Sta/Elev= 30
       0  865.85    10.5  860.99    13.8  858.59    16.7  855.56    20.4   851.4
    30.3  841.48    33.6  837.74    36.9  834.54    40.2  832.37   40.73832.2314
    43.5  831.49    46.8  831.38   323.8  831.38   327.1  831.39     331832.2316
   333.7  833.25   340.3  836.64   350.2  840.32   356.8  843.29   360.1  845.05
     370   851.4   379.6  858.39   383.2  860.78   389.8  865.51   393.1  867.66
   399.7  871.77     403  873.64   409.5  877.89   412.9  879.33     425  885.56
#Mann= 3 ,-1,0
       0      .1       0   40.73    .045       0     331      .1       0
Bank Sta=40.73,331
XS Rating Curve= 0 ,0
Exp/Cntr(USF)=0,0
Exp/Cntr=0.3,0.1

Type RM Length L Ch R = 1 ,2400    ,389.8,300,241.2
XS GIS Cut Line= 6
1665618.75032325536076.1833945071665632.95797201 536162.52213259
1665645.13609725536236.5269058351665661.37359759536335.199936837
1665673.55139476536409.2043820021665687.75937159536495.543448165
#Sta/Elev= 30
       0  866.23     6.5  862.35    19.8  852.78      23  850.91    26.4  849.33
    29.7  847.26    33.1  844.74    36.4  841.04    40.1  836.15      43  833.79
   47.97832.1411    49.7  831.41      53  831.38   342.3  831.38   345.6  831.47
  349.68832.1394   352.3  832.91   358.9  836.36   368.5  840.24   372.2  842.03
   378.9  846.13   385.6   851.4   388.8  853.05   395.5  855.35   405.5  860.16
   408.8   861.9   411.3  863.51   418.8  869.86   422.1  871.39     425  872.11
#Mann= 4 ,-1,0
       0      .1       0   47.97    .045       0  349.68     .05       0
   397.5      .1       0
Bank Sta=47.97,349.68
XS Rating Curve= 0 ,0
Exp/Cntr(USF)=0,0
Exp/Cntr=0.3,0.1

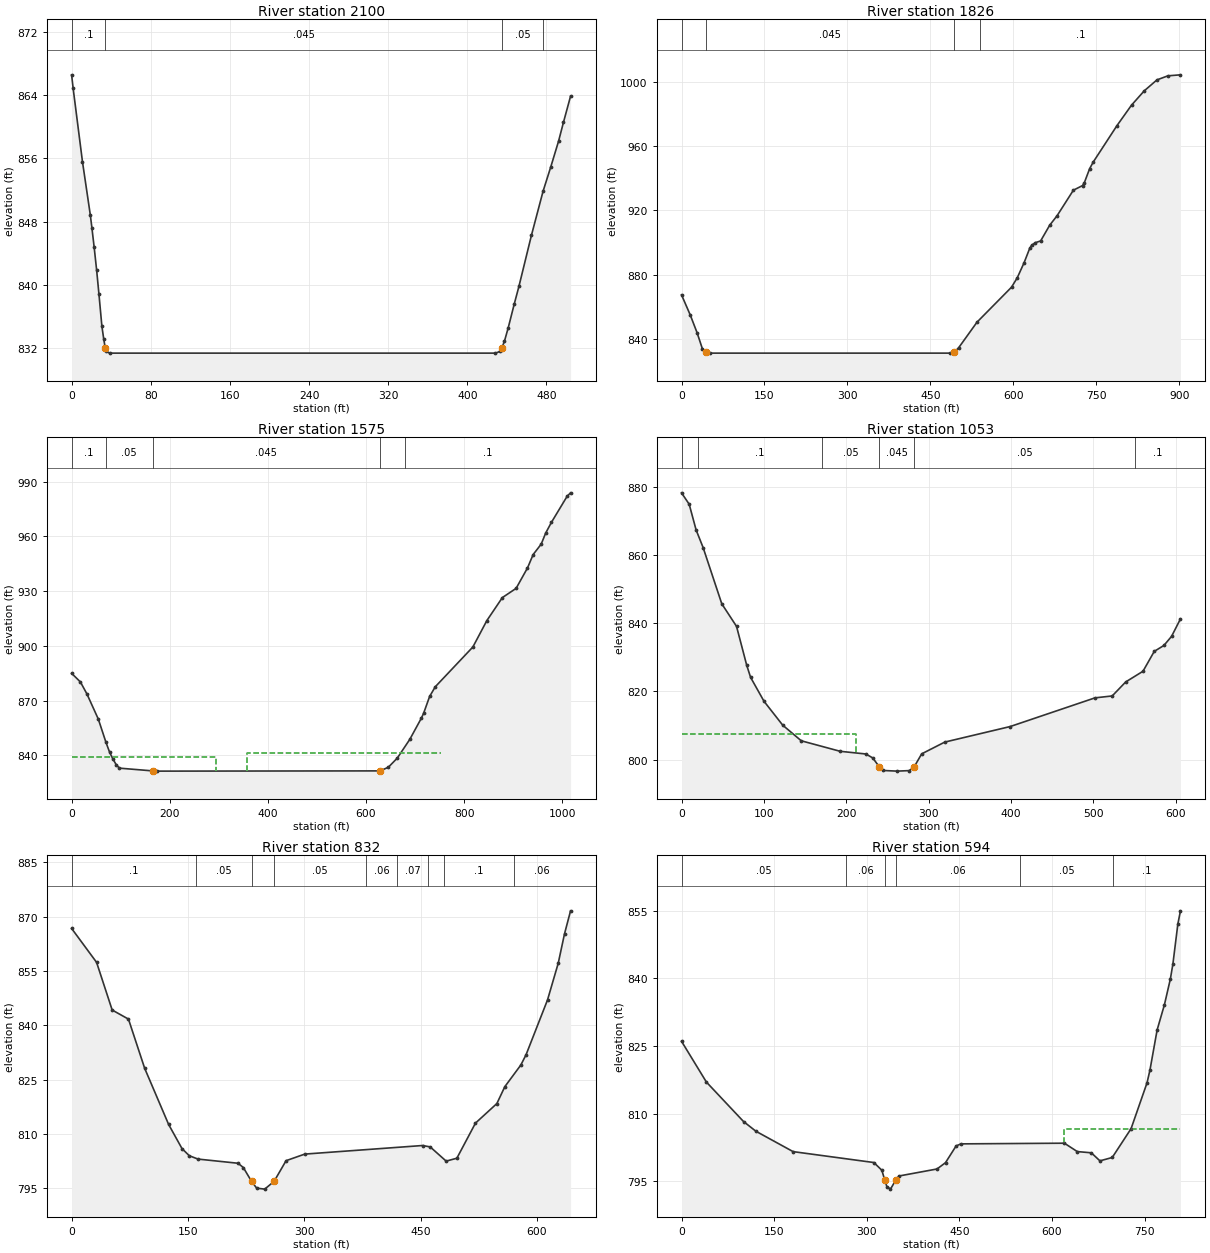
Type RM Length L Ch R = 1 ,2100    ,129,273.8,351.4
XS GIS Cut Line= 6
1665226.10974917536168.3543061071665316.53472035536308.678664416
1665357.48542584536371.5122001771665412.08702268 536455.28959167
1665453.03772818536518.1231274161665500.81387934536591.428427011
#Sta/Elev= 26
       0  866.54     1.5  864.87      11  855.54    18.9  848.84    20.5  847.22
    22.8  844.75    25.3  841.86    27.6  838.87    30.6  834.78    32.4  833.22
   33.96 832.044    34.5   831.6    38.5  831.38   428.5  831.38   433.2   831.6
  434.89832.0409   437.5  832.86   441.4  834.59   447.4  837.55   452.2  839.81
   464.9  846.29   476.6  851.83   484.5  854.95   492.3  858.17   497.2  860.53
   504.4  863.84
#Mann= 4 ,-1,0
       0      .1       0   33.96    .045       0  434.89     .05       0
  476.94      .1       0
Bank Sta=33.96,434.89
XS Rating Curve= 0 ,0
Exp/Cntr(USF)=0,0
Exp/Cntr=0.3,0.1

Type RM Length L Ch R = 1 ,1826    ,250.8,250.8,250.8
XS GIS Cut Line= 2
1665120.31103143536195.6363144071665173.44013588537096.109623771
#Sta/Elev= 30
       0   867.6    15.7  855.16    28.1  844.09    37.9  833.91   44.63831.9415
    51.1  831.38   485.9  831.38  493.01 831.942   501.2  834.82   534.2  850.62
   596.6  872.35     607  878.23   619.4  887.62   629.5  896.53   632.8   898.3
   639.3  899.97   649.2  901.08   665.6  910.86   678.8  916.67   708.4  932.61
   724.9  935.47   728.1  937.16   737.9  946.05   744.5  950.21   787.2  972.73
   813.5  985.45   836.5  994.34   859.5 1001.15   879.3 1003.67     902 1004.29
#Mann= 4 ,-1,0
       0      .1       0   44.63    .045       0  493.01     .05       0
     540      .1       0
Bank Sta=44.63,493.01
XS Rating Curve= 0 ,0
Exp/Cntr(USF)=0,0
Exp/Cntr=0.3,0.1

Type RM Length L Ch R = 1 ,1575    ,522.8,522.8,522.8
XS GIS Cut Line= 4
1665039.73913687536189.5077511441665021.13797717536315.467013363
1664692.13532523536708.4424031821664429.97246777536979.486661697
#Sta/Elev= 30
       0  884.95    17.9  880.23    31.2  873.66    54.4  859.89      70  847.16
    77.6  841.61    84.2  838.02    90.9  834.88    97.5  833.01  165.03831.5104
   174.4  831.38  628.72831.5103   645.5   833.5   663.7   838.5   689.2  848.76
   712.8  860.38   717.5  863.12   729.6  872.26   741.2  877.59   817.8  899.38
   846.3  913.84   877.9  926.44   905.9  931.48   929.1  942.67   940.7  950.03
     957   955.7   966.2  961.78   977.8   967.6    1010  981.98  1016.9  983.82
#Mann= 5 ,-1,0
       0      .1       0      70     .05       0  165.03    .045       0
  628.72     .05       0  679.84      .1       0
#XS Ineff= 2 ,-1
       0  293.72  839.36  356.97  752.06  841.12
Permanent Ineff=
       F       F
Bank Sta=165.03,628.72
XS Rating Curve= 0 ,0
Exp/Cntr(USF)=0,0
Exp/Cntr=0.3,0.1

Type RM Length L Ch R = 1 ,1053    ,208.2,220.2,229.1
XS GIS Cut Line= 2
1664591.36738375536032.6378008891664212.30286802536505.205295339
#Sta/Elev= 30
       0  878.26     9.3  874.92    17.7  867.38    26.2  862.21    48.9  845.69
    66.8  839.07    79.2  827.62    83.9  824.09   100.2  817.07   122.9  810.07
   145.4  805.49   192.6  802.41   223.8  801.62   232.2  800.46  240.25 797.817
   244.9  796.78   261.7  796.59   276.5  796.74  282.41797.8168   291.6  801.66
   319.6  805.11     399  809.67     502  818.09   522.9  818.65   539.3  822.76
   560.3   825.9     574  831.74   585.7  833.47     595  836.14   605.8  841.27
#Mann= 6 ,-1,0
       0     .05       0      20      .1       0     170     .05       0
  240.25    .045       0  282.41     .05       0     550      .1       0
#XS Ineff= 2 , 0
          211.77  807.37
Permanent Ineff=
       F       F
Bank Sta=240.25,282.41
XS Rating Curve= 0 ,0
Exp/Cntr(USF)=0,0
Exp/Cntr=0.3,0.1

Type RM Length L Ch R = 1 ,832     ,237.7,238.7,239.1
XS GIS Cut Line= 2
1664554.08441371535995.1525495811663940.53579992536188.667721714
#Sta/Elev= 30
       0  866.75    32.2  857.38    52.3  844.21    73.3   841.7    94.2   828.1
   125.1  812.58   142.3  805.93   151.7  803.95     163  803.02   214.6  801.87
   221.4  800.68  231.93796.8919   238.6  794.99     249  794.72  261.15796.8928
   276.5  802.58   300.6   804.4   452.5  806.77   462.3  806.39   482.9  802.46
   496.7  803.26   520.7  812.96   548.3  818.37   558.6  823.05   579.2  829.02
   585.9  831.84   613.6  847.01   627.4  857.14   635.5  865.27   643.3  871.62
#Mann= 9 ,-1,0
       0      .1       0     160     .05       0  231.93    .045       0
  261.15     .05       0     380     .06       0     420     .07       0
     460     .06       0     480      .1       0     570     .06       0
Bank Sta=231.93,261.15
XS Rating Curve= 0 ,0
Exp/Cntr(USF)=0,0
Exp/Cntr=0.3,0.1

Type RM Length L Ch R = 1 ,594     ,59.3,60,59.9
XS GIS Cut Line= 4
1664592.39503853535827.1819801041664419.32036899535793.624729754
1664072.37827204535898.5535590771663912.84280628536115.471578723
#Sta/Elev= 30
       0  826.07    40.3  817.02   100.4  808.27   120.5  806.11   180.7  801.59
   311.5  799.17   324.4  797.46  329.05795.3131   332.5  793.85   338.4  793.27
  347.13 795.316   352.1  796.18   413.8  797.74   427.5  799.14   444.7  802.86
   452.6  803.31     620  803.46   640.9   801.6   663.6  801.33   677.6  799.54
   697.5  800.29     728  806.68   753.8  816.83   758.5  819.62   770.2  828.58
     782  834.17   791.6  839.86   795.7  843.17   803.8  852.12     808  855.01
#Mann= 6 ,-1,0
       0     .05       0   266.3     .06       0  329.05    .045       0
  347.13     .06       0  548.76     .05       0  698.76      .1       0
#XS Ineff= 2 , 0
                          619.49          806.72
Permanent Ineff=
       F       F
Bank Sta=329.05,347.13
XS Rating Curve= 0 ,0
Exp/Cntr(USF)=0,0
Exp/Cntr=0.3,0.1

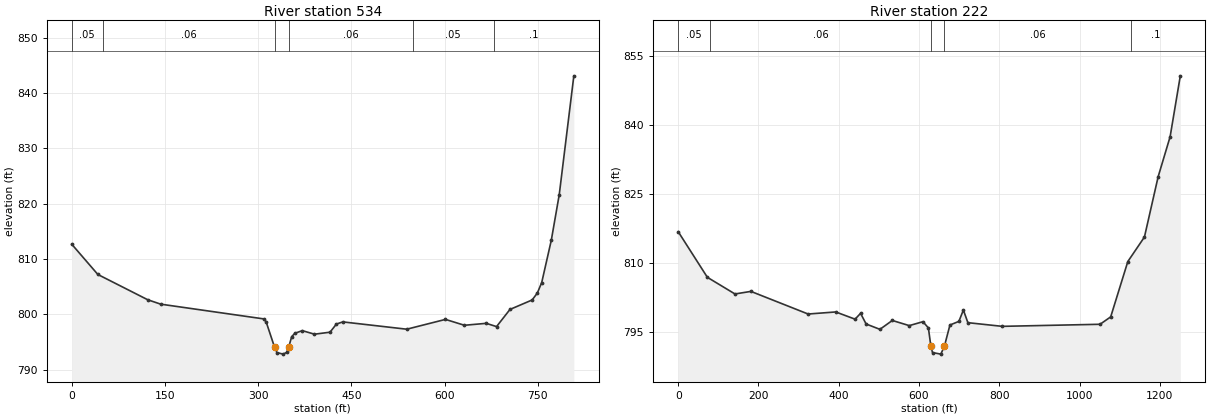
Type RM Length L Ch R = 1 ,534     ,313.3,311.3,312.6
XS GIS Cut Line= 4
1664567.85523167535772.8797854161664394.78056213535739.322535065
1664047.83846518535844.2513643881663888.30299943536061.169384034
#Sta/Elev= 30
       0  812.68      42  807.22   122.2  802.66   143.2  801.86     309   799.2
   312.8  798.67  326.41794.0674   330.1  793.12   340.2  792.84   345.9  793.16
  349.02794.0654   353.9  795.99     359   796.6     371  797.08   390.6  796.44
   415.6   796.8   425.9  798.27   436.2  798.66   539.1  797.34   601.4  799.11
   631.9  798.05   667.1   798.4   683.6  797.81   705.2  800.91   740.9  802.62
   749.3  803.88   756.3  805.77   771.7  813.39   784.5  821.63     808  843.09
#Mann= 6 ,-1,0
       0     .05       0      50     .06       0  326.41    .045       0
  349.02     .06       0  548.76     .05       0  678.76      .1       0
Bank Sta=326.41,349.02
XS Rating Curve= 0 ,0
Exp/Cntr(USF)=0,0
Exp/Cntr=0.3,0.1

Type RM Length L Ch R = 1 ,222     ,,,
XS GIS Cut Line= 6
1664612.25402291535764.853921714 1664177.7062225535627.847608404
1664103.05510952535604.4629224111664044.79214433535557.196383683
1663721.05285785 535735.998493651663587.47168853535973.493052019
#Sta/Elev= 30
       0  816.86    72.6  806.95   141.4  803.33   181.1  803.89   323.7  798.97
   392.5  799.42   440.7  797.85   454.4  799.12   468.2   796.8   502.6  795.64
   533.5  797.57   575.7  796.45   609.8   797.3   623.4  795.95  629.54791.9814
   633.7  790.59   654.4  790.25  663.34791.9808   677.1  796.58   699.4  797.37
   710.6  799.84   721.8  797.09   807.5  796.29  1051.2  796.74  1077.7  798.35
  1120.4  810.38  1161.8  815.71    1196  828.83  1225.8  837.52  1251.2  850.76
#Mann= 5 ,-1,0
       0     .05       0      80     .06       0  629.54    .045       0
  663.34     .06       0 1128.72      .1       0
Bank Sta=629.54,663.34
XS Rating Curve= 0 ,0
Exp/Cntr(USF)=0,0
Exp/Cntr=0.3,0.1
LCMann Table=0

Chan Stop Cuts=-1
Use User Specified Reach Order=0
Composite Channel Slope=5